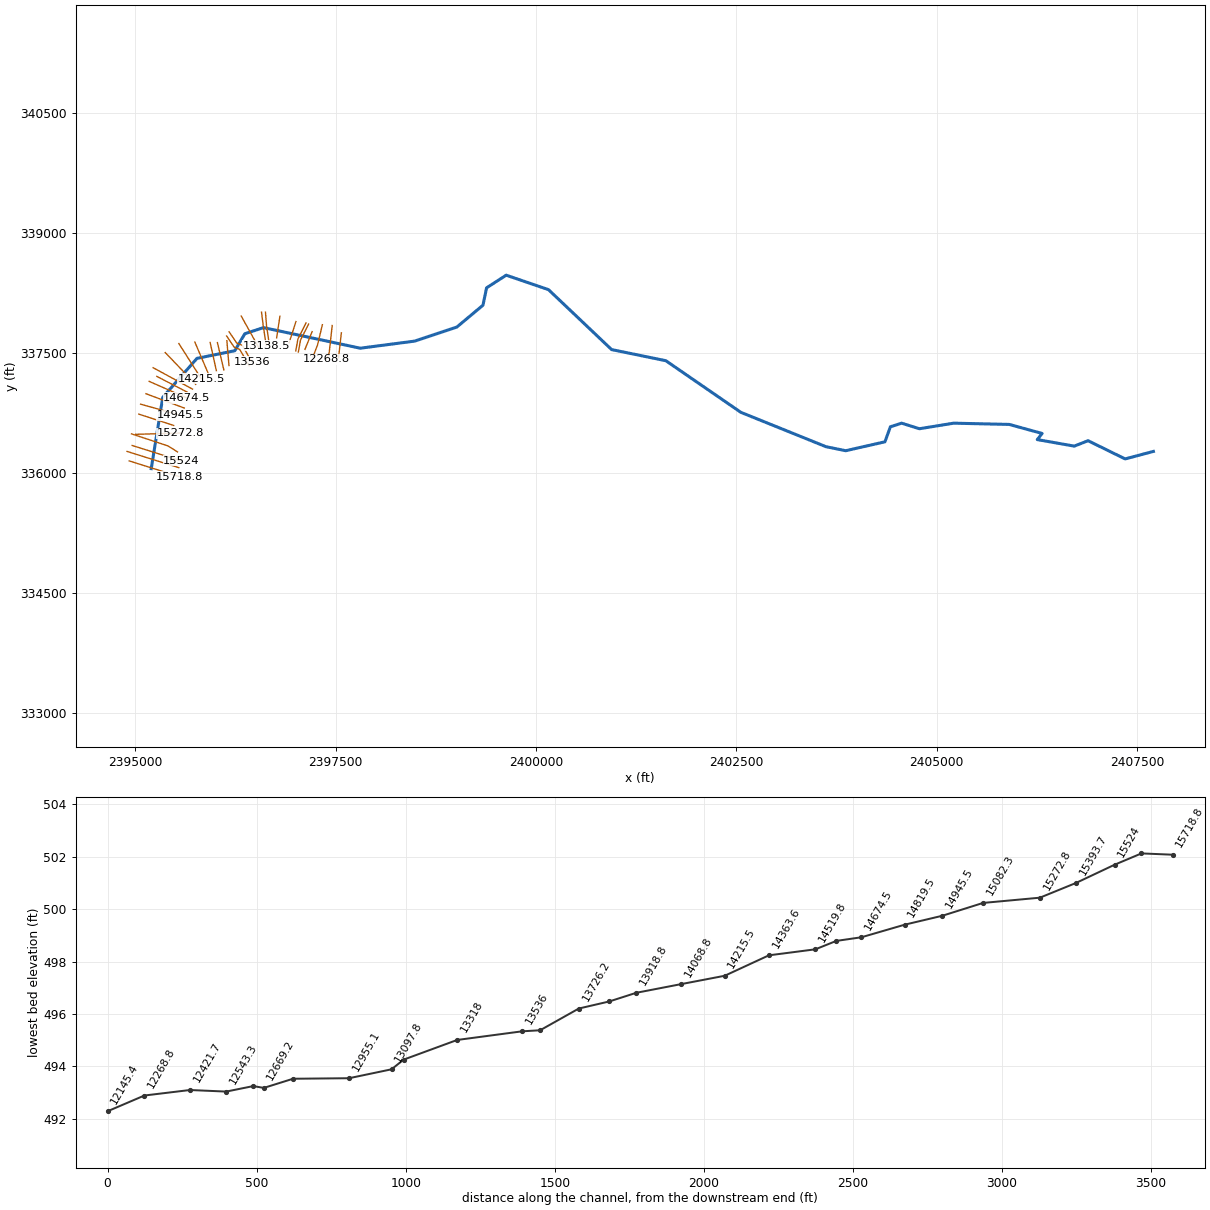
--- COLDSPRING.prj (project) ---

Proj Title=COLDSPRING
Current Plan=p01
Default Exp/Contr=0,0
English Units
Geom File=g01
Flow File=f01
Plan File=p01
BEGIN DESCRIPTION:
END DESCRIPTION:
DSS Export Rating Curves= 0
DSS Export Rating Curve Sorted= 0
DSS Export Volume Flow Curves= 0
DXF OffsetX= 0
DXF OffsetY= 0
DXF ScaleX= 0
DXF ScaleY= 0

--- COLDSPRING.p01 (plan) ---

Plan Title=Floodplain
Program Version=4.00
Geom File=g01
Flow File=f01
K Sum by GR=0
Std Step Tol=0.01
Critical Tol=0.01
Num of Std Step Trials=20
Max Error Tol=0.3
Flow Tol Ratio=0.001
Split Flow NTrial=30
Split Flow Tol=0.02
Split Flow Ratio=0.02
Log Output Level=0
Friction Slope Method=1
Unsteady Friction Slope Method=2
Unsteady Bridges Friction Slope Method=1
Global Log Level=0
CheckData=False
Run HTab=0
Run UNet=0
Run PostProcess=0
UNET Theta=0
UNET Theta Warmup=0
UNET ZTol=0
UNET ZSATol=0
UNET MxIter=0
UNET MaxInSteps=0
UNET DtIC=0
UNET DtMin=0
UNET MaxCRTS=0
UNET WFStab=0
UNET SFStab=0
UNET WFX=0
UNET SFX=0
UNET DSS MLevel=0
UNET DZMax Abort=0
UNET Convert EG Bridges=0
UNET Use Existing IB Tables=0
UNET Froude Limit=0
UNET Froude Power=0
Write IC File=0
Echo Input=False
Echo Output=False
Write Detailed=0

--- COLDSPRING.f01 (steady flow) ---

Flow Title=NFF Regression Equation
Program Version=4.00
Number of Profiles=1
Profile Names=P100yr
River Rch & RM=COLDSPRING,Main      ,15718.8
667.3433
River Rch & RM=COLDSPRING,Main      ,15524
748.4115
River Rch & RM=COLDSPRING,Main      ,14674.5
757.9531
River Rch & RM=COLDSPRING,Main      ,14068.8
855.3111
River Rch & RM=COLDSPRING,Main      ,10619.8
911.5845
River Rch & RM=COLDSPRING,Main      ,10448.3
1042.049
River Rch & RM=COLDSPRING,Main      ,7764.1
1088.633
River Rch & RM=COLDSPRING,Main      ,562.2
1209.377
River Rch & RM=COLDSPRING,Main      ,236.3
1210.570
Boundary for River Rch & Prof#=COLDSPRING,Main      ,1
Up Type=0
Dn Type=3
Dn Slope=0.009516

--- COLDSPRING.g01 (geometry) ---

Geom Title=USGS 10m DEM
Program Version=4.10

River Reach=COLDSPRING      ,Main
Reach XY= 30
     2395197.544      336055.808     2395341.642      336946.433
     2395768.725      337432.544     2396240.947       337528.03
     2396365.947      337739.835     2396598.586      337816.224
     2397806.919       337559.28     2398485.739      337647.821
     2399011.781      337823.169      2399338.17      338095.738
     2399383.308      338312.752       2399628.1      338470.738
     2400155.878      338290.183     2400944.072      337541.919
     2401621.156       337403.03     2402556.919      336758.933
      2403619.42      336330.113     2403865.947      336279.766
     2404355.531      336390.877     2404423.239      336578.377
     2404563.864      336623.516     2404786.086      336554.072
     2405213.169      336623.516     2405907.614      336607.891
     2406317.336      336495.044     2406256.572      336418.655
     2406718.378      336337.058     2406890.253      336404.766
     2407353.794      336177.335     2407706.225      336271.085

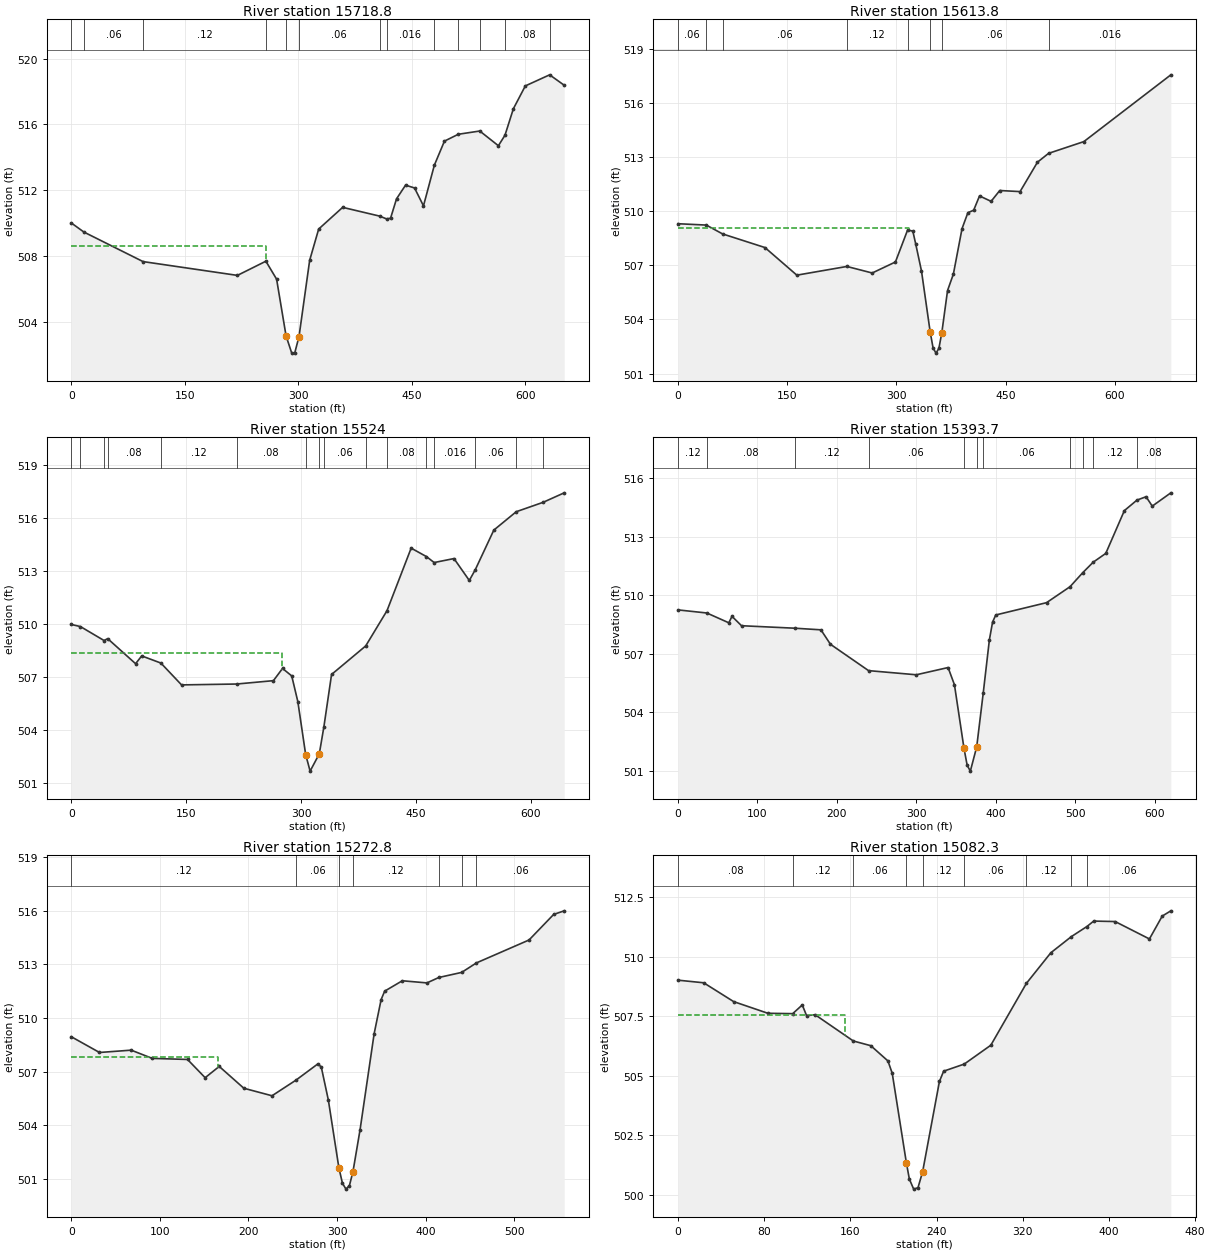
Type RM Length L Ch R = 1 ,15718.8 ,105,105,105
XS GIS Cut Line= 3
     2394922.595        336152.5     2395200.536      336065.349
     2395544.206      335957.589
#Sta/Elev= 30
       0     510   16.63509.4474   94.81  507.65   219.5  506.81  257.12507.6729
   271.3  506.58   283.8  503.13   291.3  502.08   295.2  502.08  300.92503.0886
     315  507.73   326.9  509.63   358.6  510.95  407.29510.4195   416.7510.2462
   421.9  510.29   429.8  511.47   441.7   512.3   453.6  512.13   465.4  511.04
  479.76513.5151   493.1  514.98  511.45515.3977   539.8515.5952   564.4   514.7
  573.11515.3401   584.2  516.95     600  518.34  632.13519.0144   651.4  518.38
#Mann= 13 ,-1 , 0
       0     .08       0   16.63     .06       0   94.81     .12       0
  257.12     .06       0   283.8    .045       0  300.92     .06       0
  407.29     .08       0   416.7    .016       0  479.76     .06       0
  511.45     .08       0   539.8     .06       0  573.11     .08       0
  632.13     .12       0
#XS Ineff= 2 , 0
          256.81  508.61
Permanent Ineff=
       F       F
Bank Sta=283.8,300.92
XS Rating Curve= 0 ,0
Exp/Cntr=0.3,0.1

Type RM Length L Ch R = 1 ,15613.8 ,89.8,89.8,89.8
XS GIS Cut Line= 2
     2394895.078      336271.198     2395541.038      336068.651
#Sta/Elev= 30
       0   509.3   38.93509.2252   61.39508.7335   119.5  507.98   163.3  506.45
  232.02506.9322   266.8  506.57   298.7  507.18  315.44508.9536   322.6  508.89
   326.5  508.19   334.5  506.68   346.4  503.31   350.4  502.42   354.4  502.13
   358.4  502.39   362.4  503.26   370.3   505.6   378.3  506.51   390.2  509.03
   398.2  509.91   406.2  510.05   414.2  510.84   430.1  510.54     442  511.14
   469.9  511.08   493.8  512.71  508.99513.1976   557.5  513.85     677  517.55
#Mann= 8 ,-1 , 0
       0     .06       0   38.93     .12       0   61.39     .06       0
  232.02     .12       0  315.44     .06       0   346.4    .045       0
   362.4     .06       0  508.99    .016       0
#XS Ineff= 2 , 0
          317.35  509.08
Permanent Ineff=
       F       F
Bank Sta=346.4,362.4
XS Rating Curve= 0 ,0
Exp/Cntr=0.3,0.1

Type RM Length L Ch R = 1 ,15524   ,130.6,130.3,129.9
XS GIS Cut Line= 2
     2394959.784      336345.103      2395573.63      336152.373
#Sta/Elev= 30
       0     510   11.96  509.88   42.74509.0916   47.46509.1978    83.9  507.78
    91.9  508.22  116.91 507.817   143.9  506.58  215.74506.6294   263.8  506.82
   275.7  507.51   287.7  507.09   295.7  505.63   305.9  502.64   311.7   501.7
   323.7  502.68   329.7  504.21   339.7  507.17  384.26508.7845  412.08510.7808
   443.6  514.32  463.56513.8412  473.63513.5045   499.5  513.73   519.5  512.49
  527.26513.0948   551.5  515.34  580.75516.3806  615.91516.9138   643.4  517.45
#Mann= 16 ,-1 , 0
       0     .06       0   11.96     .12       0   42.74    .016       0
   47.46     .08       0  116.91     .12       0  215.74     .08       0
   305.9    .045       0   323.7     .08       0   329.7     .06       0
  384.26     .12       0  412.08     .08       0  463.56     .06       0
  473.63    .016       0  527.26     .06       0  580.75     .08       0
  615.91     .06       0
#XS Ineff= 2 , 0
          274.62  508.39
Permanent Ineff=
       F       F
Bank Sta=305.9,323.7
XS Rating Curve= 0 ,0
Exp/Cntr=0.3,0.1

Type RM Length L Ch R = 1 ,15393.7 ,113,120.8,128.7
XS GIS Cut Line= 3
     2394951.373       336490.22       2395406.9      336339.397
     2395525.921       336265.09
#Sta/Elev= 30
       0  509.25   36.36 509.091      64  508.59      68  508.92      80  508.44
  147.05508.3129   179.9  508.23   191.9  507.49  239.82506.1424   299.9  505.93
   339.9   506.3   347.9  505.42   359.9  502.17   363.9   501.3   367.9     501
   375.9  502.24  384.08504.9803   391.9  507.73   395.9  508.63   399.9  508.99
   463.8  509.62   493.3510.4354  509.27511.1513  522.48 511.691   538.3  512.14
   561.7  514.33  577.54514.8674     589  515.04   596.8  514.56   620.2  515.24
#Mann= 11 ,-1 , 0
       0     .12       0   36.36     .08       0  147.05     .12       0
  239.82     .06       0   359.9    .045       0   375.9     .12       0
  384.08     .06       0   493.3     .12       0  509.27     .08       0
  522.48     .12       0  577.54     .08       0
Bank Sta=359.9,375.9
XS Rating Curve= 0 ,0
Exp/Cntr=0.3,0.1

Type RM Length L Ch R = 1 ,15272.8 ,198.3,190.5,181.3
XS GIS Cut Line= 2
      2395003.87      336484.363     2395560.187      336499.669
#Sta/Elev= 30
       0  508.96    31.8  508.08    67.6  508.21    91.4  507.75   131.2  507.69
   151.1  506.67     167   507.3   194.8  506.08   226.6  505.66  253.67506.5345
   278.3  507.44   282.2  507.27   290.2  505.42   302.1  501.63   306.1  500.77
   310.1  500.44     314  500.64     318  501.42     326  503.76   341.9  509.13
   349.8  511.04   353.8  511.51   373.7  512.09   401.5  511.97   414.9512.2725
  440.69512.5569  457.44513.0898   516.8  514.37   544.6   515.8   556.5     516
#Mann= 7 ,-1 , 0
       0     .12       0  253.67     .06       0   302.1    .045       0
     318     .12       0   414.9     .06       0  440.69     .12       0
  457.44     .06       0
#XS Ineff= 2 , 0
          165.33  507.81
Permanent Ineff=
       F       F
Bank Sta=302.1,318
XS Rating Curve= 0 ,0
Exp/Cntr=0.3,0.1

Type RM Length L Ch R = 1 ,15082.3 ,135.7,136.8,139.2
XS GIS Cut Line= 2
     2395042.463      336736.384     2395477.717      336595.461
#Sta/Elev= 30
       0  509.01    23.9   508.9    51.7  508.11    83.5  507.62  106.51507.6045
   115.4  507.97   119.4  507.52   127.3  507.56  162.79 506.457     179  506.26
   194.9  505.62   198.9   505.1   212.1  501.32   214.8  500.66   218.8  500.24
   222.8   500.3   227.1  500.97   242.7  504.76   246.6  505.19  265.73505.4882
   290.4  506.28  323.41508.8756   346.1  510.16  365.26510.8415  379.59511.2618
   385.9  511.49   405.8  511.47   437.6  510.74   449.5   511.7   457.5  511.92
#Mann= 9 ,-1 , 0
       0     .08       0  106.51     .12       0  162.79     .06       0
   212.1    .045       0   227.1     .12       0  265.73     .06       0
  323.41     .12       0  365.26     .08       0  379.59     .06       0
#XS Ineff= 2 , 0
          155.46  507.53
Permanent Ineff=
       F       F
Bank Sta=212.1,227.1
XS Rating Curve= 0 ,0
Exp/Cntr=0.3,0.1

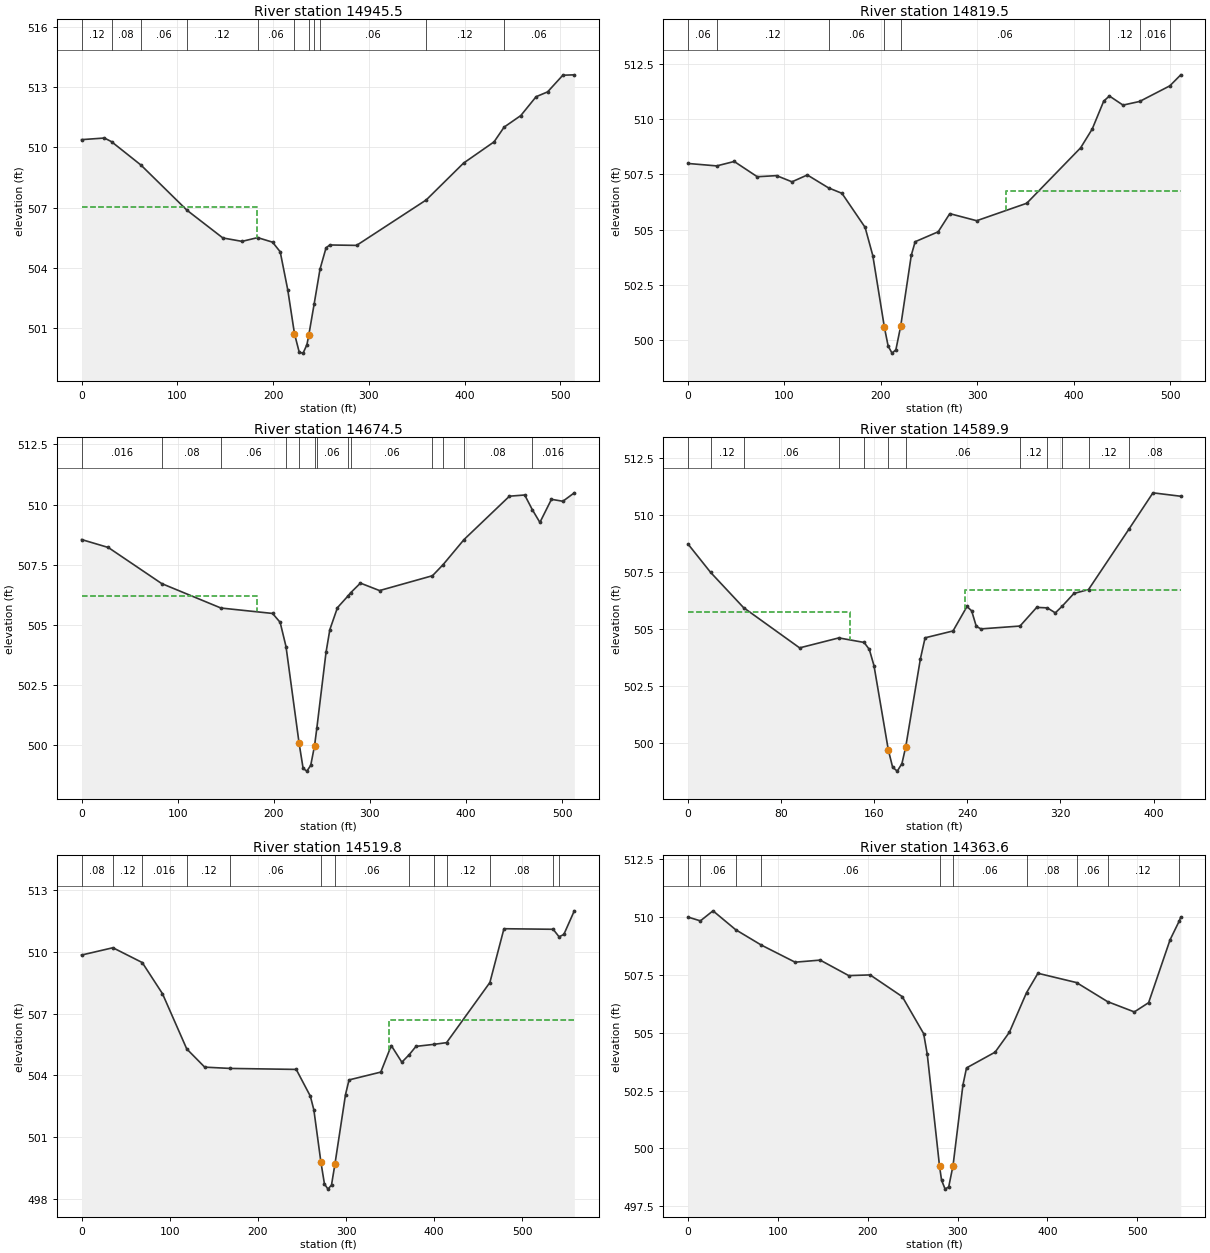
Type RM Length L Ch R = 1 ,14945.5 ,128,126,124.2
XS GIS Cut Line= 2
      2395064.71      336860.832     2395560.421      336722.344
#Sta/Elev= 30
       0  510.39    23.9  510.47    31.3 510.288   62.05509.1225  110.12506.8714
   147.6  505.49   167.6  505.32  183.96505.5066   199.5  505.28   207.5   504.8
   215.4   502.9   222.4  500.72   227.4  499.79   231.4  499.75   235.4  500.17
   237.4  500.66  243.02502.2179  249.09503.9387   255.4     505   259.3  505.14
   287.3  505.12  359.99507.3834     399  509.22   430.9  510.28  441.38 511.014
   458.8  511.59   474.8  512.53   486.8  512.77   502.7   513.6   514.7  513.62
#Mann= 11 ,-1 , 0
       0     .12       0    31.3     .08       0   62.05     .06       0
  110.12     .12       0  183.96     .06       0   222.4    .045       0
   237.4     .06       0  243.02     .12       0  249.09     .06       0
  359.99     .12       0  441.38     .06       0
#XS Ineff= 2 , 0
          183.49  507.04
Permanent Ineff=
       F       F
Bank Sta=222.4,237.4
XS Rating Curve= 0 ,0
Exp/Cntr=0.3,0.1

Type RM Length L Ch R = 1 ,14819.5 ,146.4,145.1,143.8
XS GIS Cut Line= 2
     2395131.025      336991.448      2395609.58      336812.639
#Sta/Elev= 30
       0  507.99   29.76  507.88    47.9  508.08    71.8  507.39    91.8  507.44
   107.8  507.16   123.7  507.47  145.68506.8856   159.6  506.64   183.6   505.1
   191.6  503.82   203.6  500.58   207.5  499.73   211.5  499.41   215.5  499.56
   220.5  500.63   231.5  503.84   235.5  504.45   259.4   504.9   271.4  505.72
   299.3   505.4   351.2  506.19   407.1   508.7   419.1  509.55     431  510.81
  436.87511.0427     451  510.63  468.19510.7949  499.51511.5005   510.9     512
#Mann= 8 ,-1 , 0
       0     .06       0   29.76     .12       0  145.68     .06       0
   203.6    .045       0   220.5     .06       0  436.87     .12       0
  468.19    .016       0  499.51     .06       0
#XS Ineff= 2 , 0
                          329.41          506.75
Permanent Ineff=
       F       F
Bank Sta=203.6,220.5
XS Rating Curve= 0 ,0
Exp/Cntr=0.3,0.1

Type RM Length L Ch R = 1 ,14674.5 ,85.9,84.5,83.2
XS GIS Cut Line= 2
     2395172.172      337145.112     2395641.277      336938.445
#Sta/Elev= 30
       0  508.55    27.8  508.22   83.41506.7197  145.01505.7048   198.7  505.48
   206.6  505.11   212.7504.1013   226.3  500.09   230.5  499.04   234.4  498.93
   238.4  499.17   242.4  499.99  244.72500.7034   254.3  503.86   258.3  504.81
   266.2  505.72  276.74 506.187  279.83506.3353   290.1  506.74     310  506.43
  365.06507.0471  376.13507.5081  397.92508.5508   445.1  510.35     461   510.4
  468.87509.7932   476.8  509.26   488.8  510.22   500.7  510.14   512.6  510.49
#Mann= 13 ,-1 , 0
       0    .016       0   83.41     .08       0  145.01     .06       0
   212.7     .08       0   226.3    .045       0   242.4     .08       0
  244.72     .06       0  276.74    .016       0  279.83     .06       0
  365.06     .08       0  376.13     .06       0  397.92     .08       0
  468.87    .016       0
#XS Ineff= 2 , 0
          182.48  506.21
Permanent Ineff=
       F       F
Bank Sta=226.3,242.4
XS Rating Curve= 0 ,0
Exp/Cntr=0.3,0.1

Type RM Length L Ch R = 1 ,14589.9 ,70.6,70.1,69.7
XS GIS Cut Line= 2
     2395267.487       337207.21      2395643.75      337012.962
#Sta/Elev= 30
       0  508.72   19.37507.4831    47.7 505.941    95.9  504.18  129.59504.6158
   151.3504.4175   155.8  504.11   159.8   503.4   172.1  499.72   175.8  498.96
   179.8  498.79   183.8  499.12   187.1  499.86   199.7  503.71   203.7  504.62
   227.7  504.92   239.7  505.99   243.7   505.8   247.7  505.12   251.7  505.01
  285.26505.1347   299.6  505.95  308.73505.9294   315.6  505.71  321.47506.0016
   331.6  506.56  344.13506.7296  379.22509.3997   399.5  510.96   423.4  510.81
#Mann= 12 ,-1 , 0
       0    .016       0   19.37     .12       0    47.7     .06       0
  129.59     .08       0   151.3     .06       0   172.1    .045       0
   187.1     .06       0  285.26     .12       0  308.73     .06       0
  321.47     .08       0  344.13     .12       0  379.22     .08       0
#XS Ineff= 2 , 0
           138.8  505.73  237.99          506.71
Permanent Ineff=
       F       F
Bank Sta=172.1,187.1
XS Rating Curve= 0 ,0
Exp/Cntr=0.3,0.1

Type RM Length L Ch R = 1 ,14519.8 ,163.1,156.1,149.2
XS GIS Cut Line= 2
      2395221.48      337315.827     2395712.655      337049.078
#Sta/Elev= 30
       0  509.85   35.55510.2053   68.84509.4854    91.8  507.97  119.31505.2863
   139.7   504.4  168.71504.3381   243.5  504.29   259.5  502.99   263.5  502.32
   271.5  499.78   275.5  498.72   279.5  498.47   283.5  498.67   287.4  499.69
   299.4  503.07   303.4  503.78   339.4  504.16   351.3  505.45   363.3  504.64
  371.78505.0136   379.3  505.41  399.62505.5085  414.01505.5913  463.14508.5155
   479.1  511.13  534.89511.1028   541.6 510.738     547  510.85   558.9     512
#Mann= 13 ,-1 , 0
       0     .08       0   35.55     .12       0   68.84    .016       0
  119.31     .12       0  168.71     .06       0   271.5    .045       0
   287.4     .06       0  371.78     .12       0  399.62     .06       0
  414.01     .12       0  463.14     .08       0  534.89     .12       0
   541.6     .06       0
#XS Ineff= 2 , 0
                          349.01           506.7
Permanent Ineff=
       F       F
Bank Sta=271.5,287.4
XS Rating Curve= 0 ,0
Exp/Cntr=0.3,0.1

Type RM Length L Ch R = 1 ,14363.6 ,152.6,148.2,143.8
XS GIS Cut Line= 2
     2395373.143      337504.537     2395752.669      337108.537
#Sta/Elev= 30
       0     510   13.77 509.836    27.8  510.27   53.07509.4532   81.54508.7906
   119.2  508.05   147.1  508.14   178.9  507.47   202.7   507.5   238.5  506.56
   262.3  504.96   266.3  504.07     280  499.22   282.2  498.63   286.2  498.24
   290.2  498.34     295  499.26     306  502.74     310  503.48   341.8  504.16
   357.7  505.02  376.78506.7308   389.5  507.57  432.48507.1685  467.02506.3445
   496.8   505.9   512.7   506.3   536.6  509.02  546.64509.8186   548.5     510
#Mann= 10 ,-1 , 0
       0     .12       0   13.77     .06       0   53.07     .12       0
   81.54     .06       0     280    .045       0     295     .06       0
  376.78     .08       0  432.48     .06       0  467.02     .12       0
  546.64     .06       0
Bank Sta=280,295
XS Rating Curve= 0 ,0
Exp/Cntr=0.3,0.1

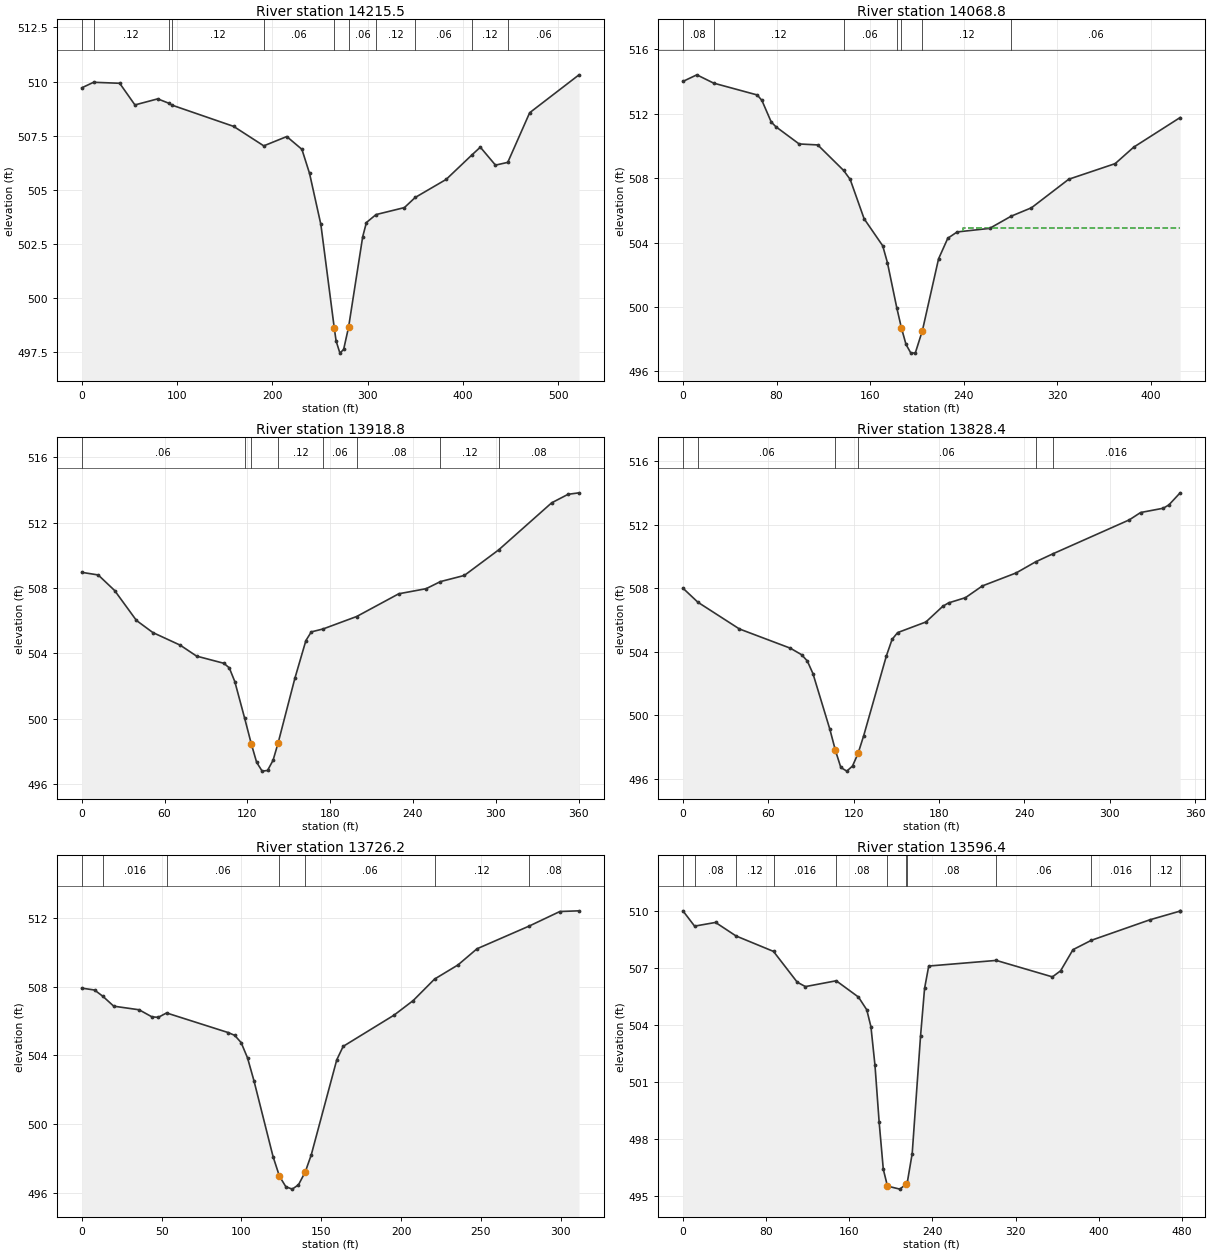
Type RM Length L Ch R = 1 ,14215.5 ,150.4,146.7,143
XS GIS Cut Line= 2
     2395542.316      337617.428     2395823.323      337177.539
#Sta/Elev= 30
       0  509.71   12.39 509.966    39.8  509.92    55.8  508.92    79.7   509.2
   91.23509.0014   94.84 508.909   159.4  507.93  191.06507.0308   215.2  507.46
   231.1  506.87   239.1  505.76     251   503.4   265.1  498.61     267  498.02
     271  497.46   274.9  497.63   280.1  498.66   294.9  502.83   298.8  503.49
  308.93503.8573   338.7  504.18  350.02504.6466   382.5  505.48  409.69506.6163
   418.4  506.97   434.3  506.14   447.2506.2682   470.2  508.56     522  510.31
#Mann= 11 ,-1 , 0
       0     .06       0   12.39     .12       0   91.23     .06       0
   94.84     .12       0  191.06     .06       0   265.1    .045       0
   280.1     .06       0  308.93     .12       0  350.02     .06       0
  409.69     .12       0   447.2     .06       0
Bank Sta=265.1,280.1
XS Rating Curve= 0 ,0
Exp/Cntr=0.3,0.1

Type RM Length L Ch R = 1 ,14068.8 ,154.2,150,145.8
XS GIS Cut Line= 2
      2395742.26      337635.497     2395908.922      337244.706
#Sta/Elev= 30
       0     514    11.9  514.41   26.26513.8947    63.5  513.16    67.5  512.82
    75.4  511.49    79.4  511.19    99.3  510.12   115.2  510.06   137.3 508.476
   142.9  507.92   154.8  505.48   170.7   503.8   174.7  502.76  182.73 499.949
   186.6  498.73   190.6  497.68   194.6  497.16   198.5  497.14   204.6  498.54
   218.4  502.99   226.3  504.27   234.3  504.66     262  504.88  280.48505.6396
   297.8  506.16   329.6  507.93   369.3   508.9   385.1  509.92   424.8  511.76
#Mann= 7 ,-1 , 0
       0     .08       0   26.26     .12       0   137.3     .06       0
  182.73     .12       0   186.6    .045       0   204.6     .12       0
  280.48     .06       0
#XS Ineff= 2 , 0
                          239.42          504.89
Permanent Ineff=
       F       F
Bank Sta=186.6,204.6
XS Rating Curve= 0 ,0
Exp/Cntr=0.3,0.1

Type RM Length L Ch R = 1 ,13918.8 ,90.1,90.4,90.7
XS GIS Cut Line= 2
     2395932.893      337630.981     2396010.512      337279.107
#Sta/Elev= 30
       0  508.96    11.9   508.8    23.8  507.85    39.6  506.02    51.5  505.28
    71.3  504.51    83.2  503.84     103   503.4   106.9  503.12   110.9  502.28
  118.01500.0469   122.8  498.49   126.7  497.35   130.7  496.81   134.6  496.85
   138.6  497.47   142.2  498.51   154.4  502.48   162.4  504.79   166.3  505.32
  174.89505.5007  199.19506.2606   229.7  507.65   249.5  507.96  259.87 508.394
   277.2  508.77  302.07510.3319   340.5  513.21   352.4  513.73   360.3  513.82
#Mann= 8 ,-1 , 0
       0     .06       0  118.01     .12       0   122.8    .045       0
   142.2     .12       0  174.89     .06       0  199.19     .08       0
  259.87     .12       0  302.07     .08       0
Bank Sta=122.8,142.2
XS Rating Curve= 0 ,0
Exp/Cntr=0.3,0.1

Type RM Length L Ch R = 1 ,13828.4 ,105.5,102.2,98.8
XS GIS Cut Line= 2
     2396023.903      337628.748     2396103.963      337288.537
#Sta/Elev= 30
       0     508   10.56507.1105    39.7  505.43    75.5  504.22    83.4  503.81
    87.4  503.42    91.4  502.62   103.3  499.11   107.2  497.78     111  496.71
   115.2  496.48   119.2   496.8   123.1  497.59   127.1  498.72     143  503.73
     147  504.77   150.9   505.2   170.8  505.87   182.7  506.86   186.7  507.07
   198.6   507.4   210.5  508.14   234.3  508.96  247.83509.6515  260.02510.1593
   313.8   512.3   321.7  512.76   337.6  513.03   341.6  513.24   349.5     514
#Mann= 6 ,-1 , 0
       0    .016       0   10.56     .06       0   107.2    .045       0
   123.1     .06       0  247.83     .08       0  260.02    .016       0
Bank Sta=107.2,123.1
XS Rating Curve= 0 ,0
Exp/Cntr=0.3,0.1

Type RM Length L Ch R = 1 ,13726.2 ,104.8,129.9,154.9
XS GIS Cut Line= 2
     2396141.592      337653.543     2396167.978      337343.261
#Sta/Elev= 30
       0  507.91       8   507.8   13.27507.4298      20  506.86    35.9  506.65
    43.9  506.24    47.9  506.21   53.11506.4651    91.8  505.32    95.8  505.16
    99.8  504.74   103.8  503.85   107.8  502.53   119.8   498.1   123.8  496.96
   127.8  496.35   131.8  496.21   135.7  496.46     140  497.22   143.7   498.2
   159.7  503.74   163.7  504.52   195.6  506.34   207.6  507.19  220.93508.4365
   235.6  509.26   247.5   510.2  280.26511.5261   299.4  512.37   311.4  512.41
#Mann= 7 ,-1 , 0
       0     .12       0   13.27    .016       0   53.11     .06       0
   123.8    .045       0     140     .06       0  220.93     .12       0
  280.26     .08       0
Bank Sta=123.8,140
XS Rating Curve= 0 ,0
Exp/Cntr=0.3,0.1

Type RM Length L Ch R = 1 ,13596.4 ,60.6,60.3,60.4
XS GIS Cut Line= 4
     2396138.626      337711.765     2396233.299      337571.839
     2396303.155      337543.142     2396419.461      337340.146
#Sta/Elev= 30
       0     510   11.24509.1958    31.4  509.39   51.11508.6797   87.16507.8682
     110  506.25   117.9  506.02  147.49506.3253   168.9  505.47   176.9   504.8
   180.9  503.91   184.8  501.88   188.8   498.9   192.8  496.42   196.8  495.54
   208.7  495.38   214.5  495.63  215.98495.7639   220.6  497.25   228.6   503.4
   232.5  505.92   236.5   507.1  301.49507.3949   355.5  506.53   363.4  506.85
   375.3  507.96  393.02508.4528  449.32509.5297  477.94509.9804   478.4     510
#Mann= 12 ,-1 , 0
       0     .06       0   11.24     .08       0   51.11     .12       0
   87.16    .016       0  147.49     .08       0   196.8    .045       0
   214.5     .12       0  215.98     .08       0  301.49     .06       0
  393.02    .016       0  449.32     .12       0  477.94    .016       0
Bank Sta=196.8,214.5
XS Rating Curve= 0 ,0
Exp/Cntr=0.3,0.1

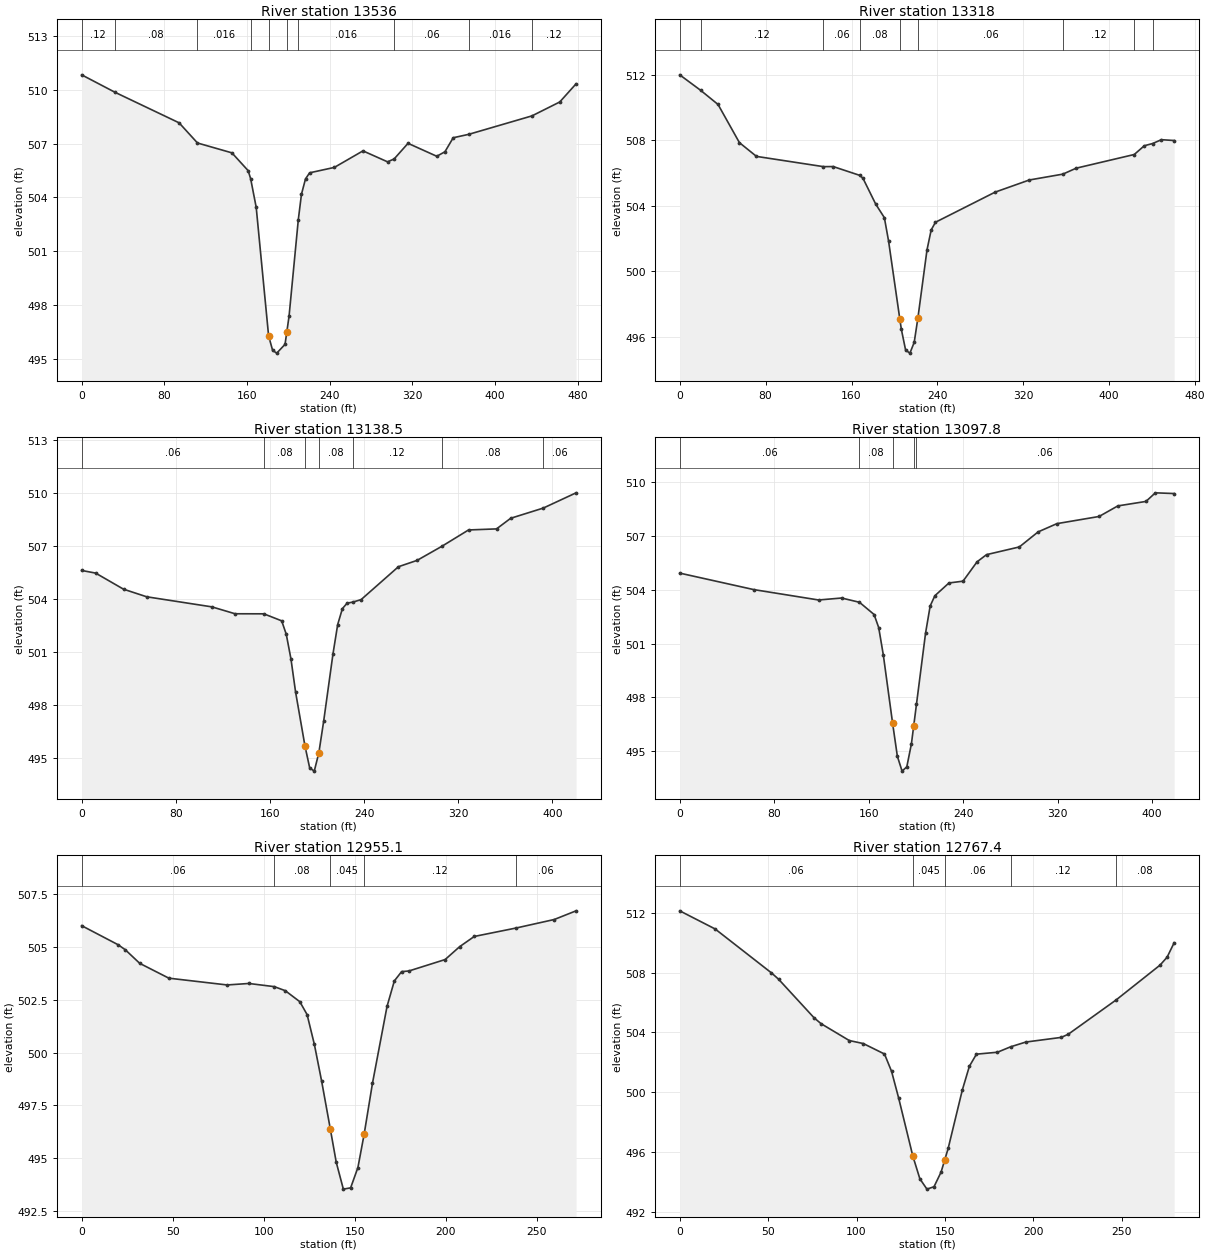
Type RM Length L Ch R = 1 ,13536   ,233,218,202.8
XS GIS Cut Line= 4
      2396170.13      337763.544     2396264.803      337623.618
     2396334.659      337594.922     2396450.965      337391.926
#Sta/Elev= 30
       0  510.82   32.36509.8468    94.3  508.15   112.1507.0277   145.4  506.48
   161.1  505.49  163.52505.0432   168.9  503.45   180.9   496.3   184.8  495.49
   188.8  495.34   196.8  495.83   198.5  496.51   200.7   497.4  209.64502.7647
   212.7  504.18   216.6  505.03   220.6  505.37   244.5  505.67   272.2  506.59
     296  505.98  302.35506.1404   315.8  507.01   343.6  506.29   351.5  506.54
   359.5  507.32  374.63507.5114  435.76508.5372   462.6  509.31   478.4  510.32
#Mann= 10 ,-1 , 0
       0     .12       0   32.36     .08       0   112.1    .016       0
  163.52     .08       0   180.9    .045       0   198.5     .12       0
  209.64    .016       0  302.35     .06       0  374.63    .016       0
  435.76     .12       0
Bank Sta=180.9,198.5
XS Rating Curve= 0 ,0
Exp/Cntr=0.3,0.1

Type RM Length L Ch R = 1 ,13318   ,187.7,179.5,171.5
XS GIS Cut Line= 2
     2396321.424       337959.97     2396544.828      337557.251
#Sta/Elev= 30
       0     512   19.48511.0548    35.7  510.19    55.6  507.86    71.5  507.02
  133.87506.3943   142.9   506.4  167.94505.8569   170.7  505.68   182.6   504.1
   190.6  503.28   194.5  501.86  205.01 497.083   206.4  496.47   210.4  495.19
   214.4  495.01   218.4  495.67   221.8  497.14   230.3  501.31   234.2  502.53
   238.2     503   293.8  504.84   325.6  505.58  356.85505.9376   369.2   506.3
  423.33507.1359   432.7  507.67  440.48507.8073   448.6  508.04   460.5  507.99
#Mann= 9 ,-1 , 0
       0     .06       0   19.48     .12       0  133.87     .06       0
  167.94     .08       0  205.01    .045       0   221.8     .06       0
  356.85     .12       0  423.33     .06       0  440.48    .016       0
Bank Sta=205.01,221.8
XS Rating Curve= 0 ,0
Exp/Cntr=0.3,0.1

Type RM Length L Ch R = 1 ,13138.5 ,40.9,40.7,40.7
XS GIS Cut Line= 3
     2396574.203      338008.712     2396596.114      337836.189
     2396632.743      337592.661
#Sta/Elev= 30
       0  505.61    11.9  505.46    35.6  504.55    55.3  504.12   110.7  503.55
   130.4  503.16  154.82503.1568     170  502.76   173.9     502   177.9   500.6
   181.8  498.74   189.8  495.68   193.8  494.44   197.7  494.26   201.6   495.3
   205.7  497.09   213.6  500.89   217.6  502.55   221.6  503.45   225.6  503.76
  230.47503.8197   237.5  503.96   269.2  505.82   285.1  506.18  306.04 506.972
   328.8   507.9   352.6  507.96   364.6  508.56  392.28509.1367   420.2     510
#Mann= 7 ,-1 , 0
       0     .06       0  154.82     .08       0   189.8    .045       0
   201.6     .08       0  230.47     .12       0  306.04     .08       0
  392.28     .06       0
Bank Sta=189.8,201.6
XS Rating Curve= 0 ,0
Exp/Cntr=0.3,0.1

Type RM Length L Ch R = 1 ,13097.8 ,149.1,142.6,135.9
XS GIS Cut Line= 3
     2396623.679      338008.805     2396637.007      337836.921
     2396673.637      337593.393
#Sta/Elev= 30
       0  504.94    62.7  504.02   117.6  503.44   137.1  503.55  152.21503.3124
   164.6  502.63   168.5   501.9   172.4  500.38   180.3  496.55   184.3  494.72
   188.3  493.89   192.3  494.13   196.2  495.41   198.1  496.39  200.47497.6131
   208.2   501.6   212.1  503.11   216.1  503.68     228  504.39   239.9  504.49
   251.8  505.57   259.8  505.97   287.6   506.4   303.5  507.24   319.4   507.7
   355.1   508.1     371  508.69   394.8  508.94   402.8  509.42   418.7  509.38
#Mann= 5 ,-1 , 0
       0     .06       0  152.21     .08       0   180.3    .045       0
   198.1     .08       0  200.47     .06       0
Bank Sta=180.3,198.1
XS Rating Curve= 0 ,0
Exp/Cntr=0.3,0.1

Type RM Length L Ch R = 1 ,12955.1 ,191.4,187.7,184.1
XS GIS Cut Line= 2
     2396803.677      337958.277     2396763.383      337689.772
#Sta/Elev= 30
       0  505.99      20  505.09      24  504.85    31.9  504.21    47.9  503.51
    79.9  503.19    91.8  503.26  105.79503.1101   111.8  502.92   119.8   502.4
   123.8  501.79   127.8  500.38   131.8  498.64  136.52496.4026   139.8  494.82
   143.7  493.55   147.7  493.61   151.7  494.57   155.1  496.13   159.7  498.55
   167.7  502.18   171.7  503.38   175.7  503.82   179.7  503.85   199.6  504.39
   207.6     505   215.6  505.48  238.72505.8812   259.5  506.28   271.5  506.69
#Mann= 5 ,-1 , 0
       0     .06       0  105.79     .08       0  136.52    .045       0
   155.1     .12       0  238.72     .06       0
Bank Sta=136.52,155.1
XS Rating Curve= 0 ,0
Exp/Cntr=0.3,0.1

Type RM Length L Ch R = 1 ,12767.4 ,101.7,98.2,94.7
XS GIS Cut Line= 2
     2397003.756      337891.749     2396918.135      337625.588
#Sta/Elev= 30
       0  512.13      20  510.92    51.9  507.98    55.9  507.56    75.9  504.99
    79.9  504.59    95.9  503.46   103.8  503.26   115.8  502.56   119.8   501.4
   123.8  499.62   131.8  495.75   135.8  494.22   139.8  493.53   143.8  493.69
   147.8  494.67   149.8  495.46   151.8  496.25   159.8  500.15   163.8  501.74
   167.8  502.55   179.7  502.68  187.06503.0396   195.7  503.36   215.7  503.67
   219.7  503.88  246.78506.1744   271.6   508.5   275.6  509.03   279.6     510
#Mann= 5 ,-1 , 0
       0     .06       0   131.8    .045       0   149.8     .06       0
  187.06     .12       0  246.78     .08       0
Bank Sta=131.8,149.8
XS Rating Curve= 0 ,0
Exp/Cntr=0.3,0.1

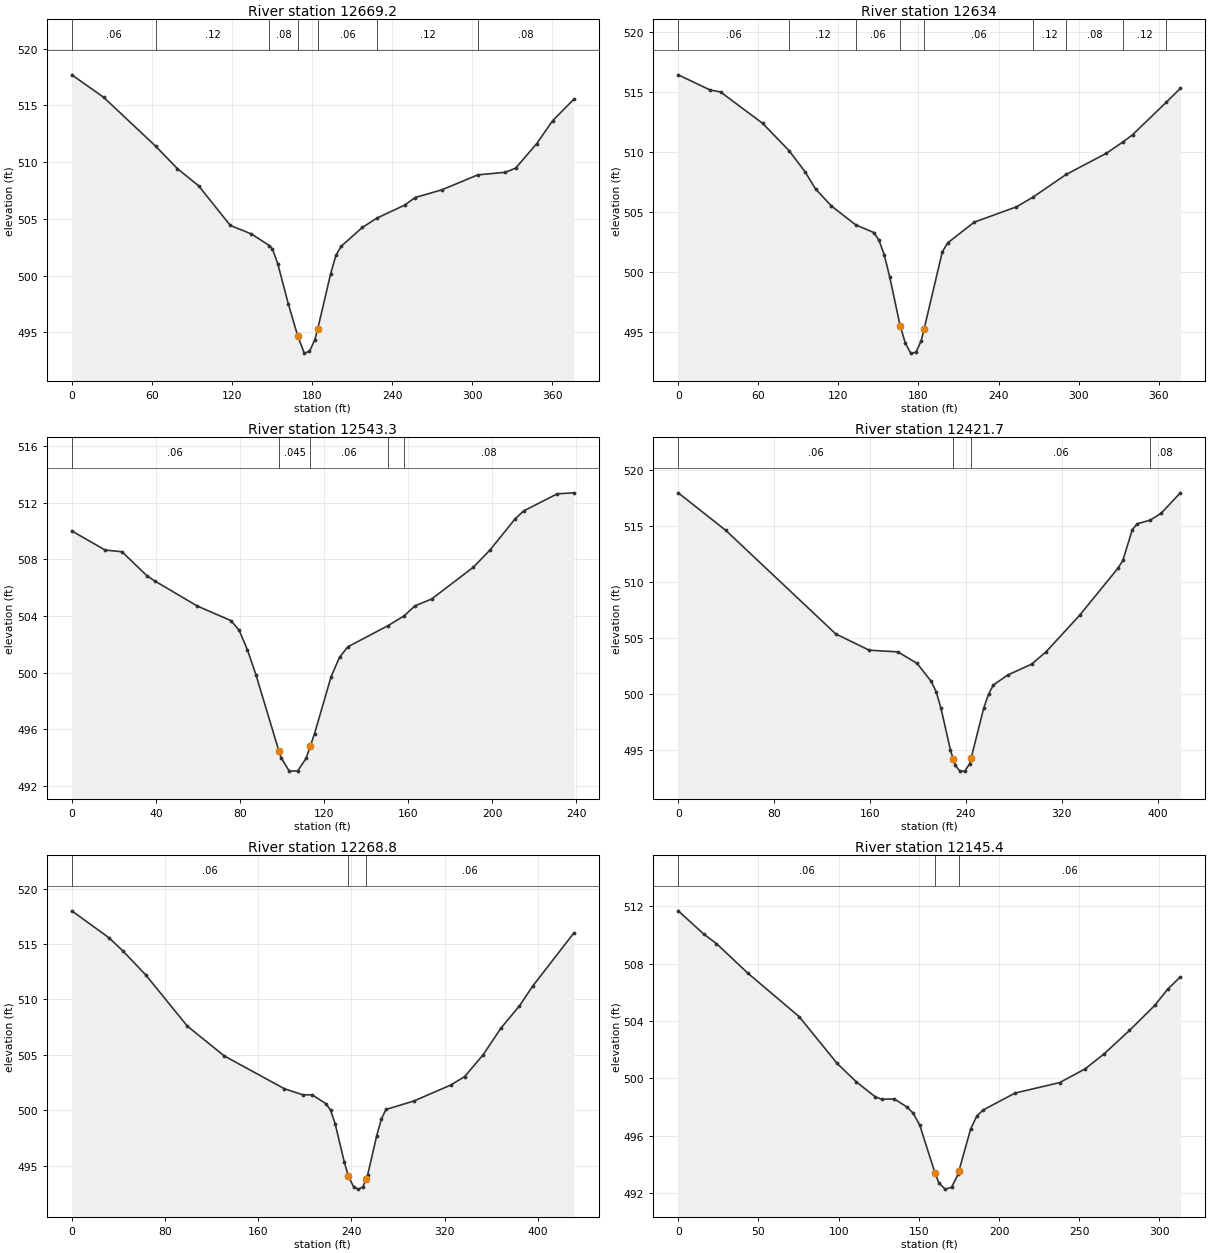
Type RM Length L Ch R = 1 ,12669.2 ,35.3,35.3,35.3
XS GIS Cut Line= 3
      2397129.71      337875.412     2397028.425       337673.77
      2397001.71      337525.663
#Sta/Elev= 30
       0   517.7    23.8  515.73   62.92511.4058    79.2  509.43      95  507.93
   118.8  504.43   134.6  503.68  148.02502.6612   150.4  502.35   154.4  501.03
   162.3   497.5   169.3   494.7   174.2  493.18   178.1  493.33   182.1  494.34
   184.3  495.32     194  500.19   197.9  501.79   201.9   502.6   217.7  504.25
  228.65505.0778   249.4  506.22   257.3  506.89   277.1  507.56  304.31508.8882
   324.7  509.11   332.6  509.48   348.4  511.64   360.3  513.66   376.2  515.55
#Mann= 7 ,-1 , 0
       0     .06       0   62.92     .12       0  148.02     .08       0
   169.3    .045       0   184.3     .06       0  228.65     .12       0
  304.31     .08       0
Bank Sta=169.3,184.3
XS Rating Curve= 0 ,0
Exp/Cntr=0.3,0.1

Type RM Length L Ch R = 1 ,12634   ,88.8,90.7,92.5
XS GIS Cut Line= 3
     2397162.047      337861.345     2397060.762      337659.703
     2397034.047      337511.596
#Sta/Elev= 30
       0  516.46    23.8   515.2    31.7  515.03    63.3  512.41   83.07510.1336
      95  508.38   102.9  506.94   114.8  505.52  133.01503.9456   146.5  503.31
   150.4  502.67   154.4  501.44   158.4  499.63   166.3  495.52   170.2  494.07
   174.2  493.25   178.1  493.31   182.1   494.3   184.3   495.3   197.9  501.71
   201.9  502.44   221.7  504.17   253.4  505.45  265.69506.2492   290.6 508.148
   320.7  509.91  333.27 510.865   340.5  511.47  365.66514.1695   376.2  515.32
#Mann= 9 ,-1 , 0
       0     .06       0   83.07     .12       0  133.01     .06       0
   166.3    .045       0   184.3     .06       0  265.69     .12       0
   290.6     .08       0  333.27     .12       0  365.66     .08       0
Bank Sta=166.3,184.3
XS Rating Curve= 0 ,0
Exp/Cntr=0.3,0.1

Type RM Length L Ch R = 1 ,12543.3 ,118.2,121.6,124.9
XS GIS Cut Line= 2
     2397205.785      337766.093     2397116.361      337544.528
#Sta/Elev= 30
       0     510    15.9  508.65    23.9  508.53    35.8  506.83    39.8  506.44
    59.7   504.7    75.7  503.67    79.6     503    83.6   501.6    87.6  499.86
    98.5  494.49    99.6  493.99   103.5  493.04   107.5  493.06   111.5  493.94
   113.5  494.81   115.5  495.68   123.4  499.71   127.4  501.08   131.4  501.82
  150.59503.3214  158.12503.9995   163.3  504.71   171.2  505.19   191.1  507.44
   199.1  508.67     211  510.86     215  511.41     231  512.62   238.9  512.69
#Mann= 5 ,-1 , 0
       0     .06       0    98.5    .045       0   113.5     .06       0
  150.59     .12       0  158.12     .08       0
Bank Sta=98.5,113.5
XS Rating Curve= 0 ,0
Exp/Cntr=0.3,0.1

Type RM Length L Ch R = 1 ,12421.7 ,150,152.9,155.7
XS GIS Cut Line= 3
     2397333.768      337852.537     2397273.644      337600.575
     2397216.525      337451.187
#Sta/Elev= 30
       0     518    39.8  514.63   131.5  505.37   159.4  503.92   183.3  503.77
   199.3  502.74   211.2  501.12   215.2  500.22   219.2  498.75   227.2  494.98
   229.5  494.18   231.1  493.62   235.1   493.1   239.1   493.1   243.1  493.74
   244.5  494.29     255  498.76     259     500     263  500.81     275   501.7
     295  502.68     307  503.78     335  507.05     367  511.26     371  511.95
     379  514.71     383  515.23   393.7515.5485     403  516.17     419     518
#Mann= 4 ,-1 , 0
       0     .06       0   229.5    .045       0   244.5     .06       0
   393.7     .08       0
Bank Sta=229.5,244.5
XS Rating Curve= 0 ,0
Exp/Cntr=0.3,0.1

Type RM Length L Ch R = 1 ,12268.8 ,123.4,123.4,123.3
XS GIS Cut Line= 3
     2397456.352      337842.464     2397418.517      337499.425
     2397383.732      337420.919
#Sta/Elev= 30
       0     518    31.7  515.59    43.6  514.41    63.5  512.22    99.2   507.6
   130.9  504.91   182.5  501.95   198.3   501.4   206.3   501.4   218.2   500.6
   222.2     500   226.1  498.79     234  495.31   237.5  494.05     242  493.08
     246  492.89   249.9  493.09   252.5  493.77   253.9  494.13   261.8  497.72
   265.8  499.23   269.8  500.08   293.6  500.84   325.3  502.28   337.2  503.04
   352.9  504.98   368.5  507.43   384.2  509.41   395.9  511.24     431     516
#Mann= 3 ,-1 , 0
       0     .06       0   237.5    .045       0   252.5     .06       0
Bank Sta=237.5,252.5
XS Rating Curve= 0 ,0
Exp/Cntr=0.3,0.1

Type RM Length L Ch R = 1 ,12145.4 ,113.3,115.1,117
XS GIS Cut Line= 2
     2397570.958      337751.797     2397535.705      337440.745
#Sta/Elev= 30
       0  511.67    15.8  510.06    23.8  509.39    43.6  507.31    75.3  504.31
    99.1  501.04     111  499.76   122.8  498.72   126.8  498.55   134.7  498.57
   142.6  498.01   146.6  497.57   150.6  496.73     160  493.44   162.5  492.72
   166.4  492.29   170.4  492.42   174.4  493.31     175  493.56   182.3  496.48
   186.2  497.39   190.2  497.81     210  498.98   237.8  499.71   253.6  500.66
   265.5  501.71   281.3  503.34   297.2   505.1   305.1  506.21     313  507.07
#Mann= 3 ,-1 , 0
       0     .06       0     160    .045       0     175     .06       0
Bank Sta=160,175
XS Rating Curve= 0 ,0
Exp/Cntr=0.3,0.1