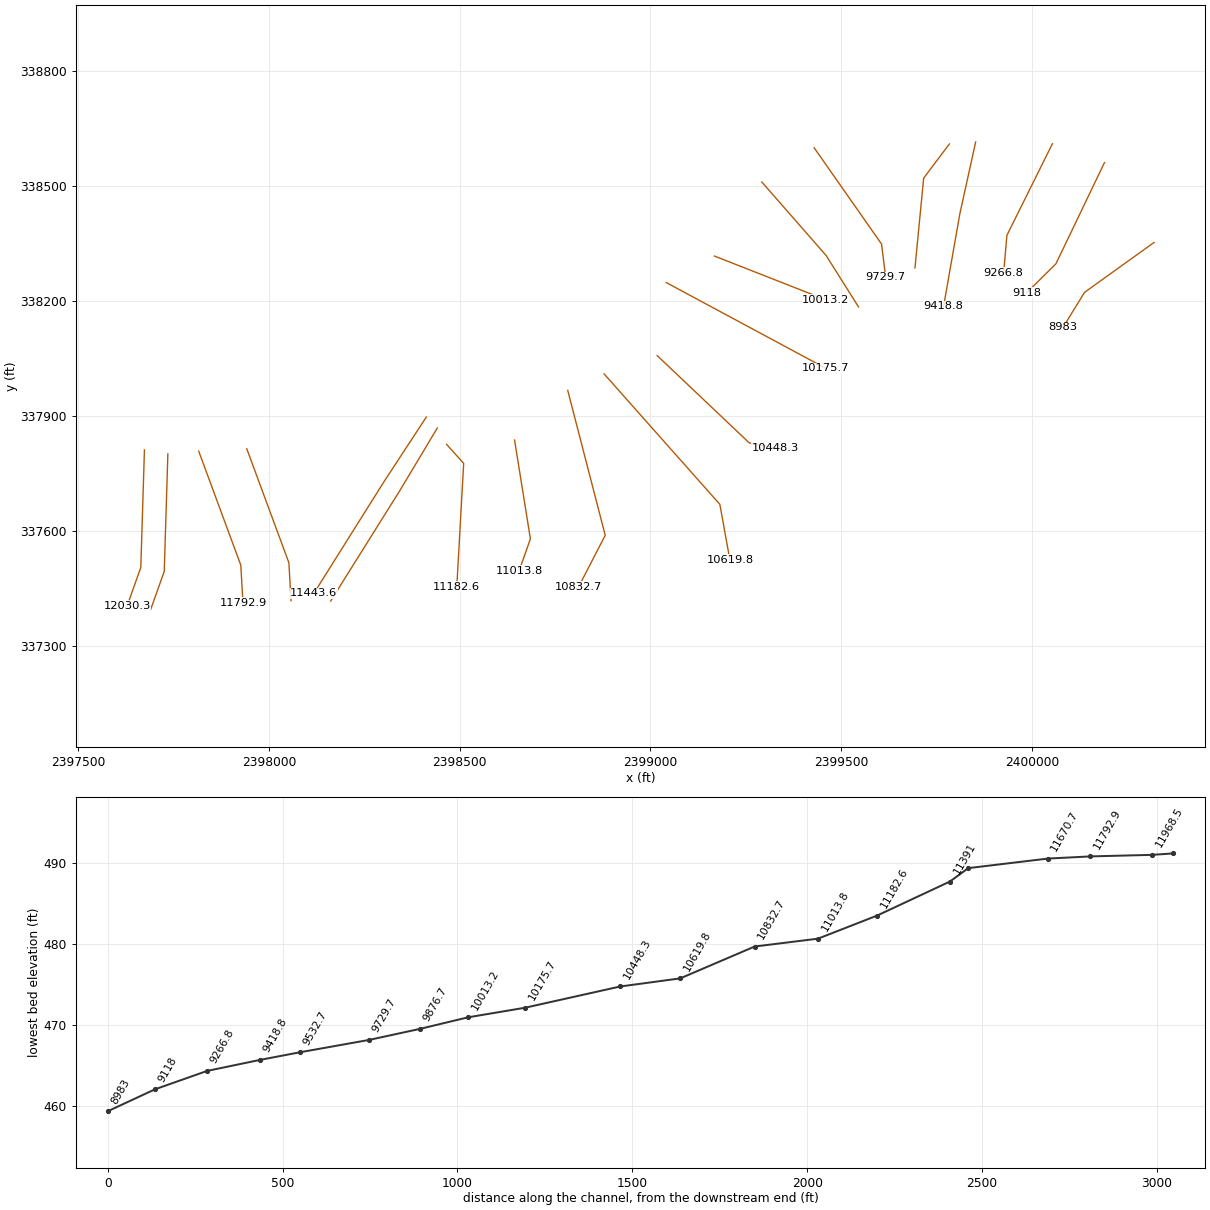
HEC-RAS study COLDSPRING.prj: COLDSPRING

--- COLDSPRING.g01 (geometry) --- (continued)

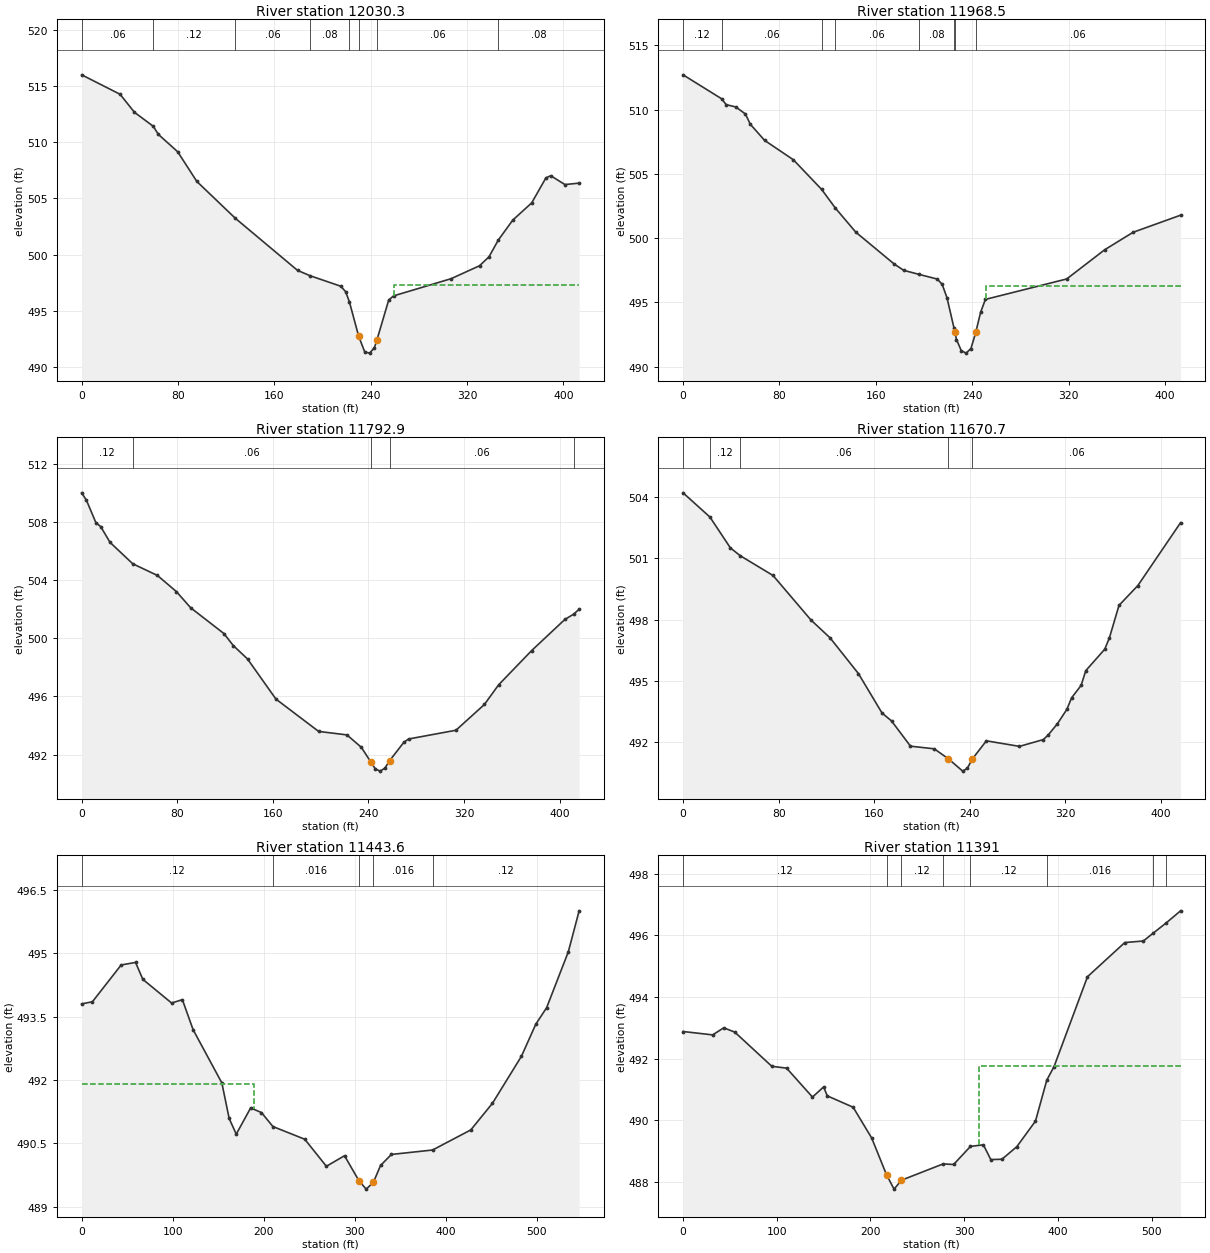
Type RM Length L Ch R = 1 ,12030.3 ,61.8,61.8,61.8
XS GIS Cut Line= 3
      2397673.93      337810.721     2397664.424      337504.152
     2397628.604      337404.082
#Sta/Elev= 30
       0  515.99    31.9  514.26    43.8  512.66   59.43511.4152    63.7  510.69
    79.7  509.15    95.6  506.51  127.56503.2334   179.2   498.6  189.59498.1244
   215.1  497.19   219.1  496.71  222.22495.8208     230  492.73     235  491.35
     239  491.24     243  491.71     245  492.37   254.9  495.96   258.9  496.33
   306.7  497.86   330.3  499.01   338.2  499.81  345.78 501.276   357.9  503.07
   373.6   504.6   385.4  506.82   389.4  507.02   401.2  506.23     413  506.36
#Mann= 8 ,-1 , 0
       0     .06       0   59.43     .12       0  127.56     .06       0
  189.59     .08       0  222.22     .06       0     230    .045       0
     245     .06       0  345.78     .08       0
#XS Ineff= 2 , 0
                          259.03           497.3
Permanent Ineff=
       F       F
Bank Sta=230,245
XS Rating Curve= 0 ,0
Exp/Cntr=0.3,0.1

Type RM Length L Ch R = 1 ,11968.5 ,166.9,175.6,184.4
XS GIS Cut Line= 3
     2397735.334      337800.413     2397725.828      337493.844
     2397690.008      337393.774
#Sta/Elev= 30
       0  512.71   32.01510.8467    35.8  510.39    43.8  510.21    51.8  509.66
    55.8  508.87    67.7  507.61    91.6   506.1  115.02503.7972  126.51502.3362
   143.4  500.47   175.3  497.99   183.2   497.5  195.94497.1848   211.1  496.82
   215.1  496.41   219.1  495.37  224.86493.0397   225.6  492.72     227  492.11
     231  491.25     235  491.06     239  491.42     243  492.68     247  494.23
     251  495.24   318.5  496.83     350   499.1   373.6  500.46     413  501.79
#Mann= 8 ,-1 , 0
       0     .12       0   32.01     .06       0  115.02     .12       0
  126.51     .06       0  195.94     .08       0  224.86     .06       0
   225.6    .045       0     243     .06       0
#XS Ineff= 2 , 0
                          251.29          496.29
Permanent Ineff=
       F       F
Bank Sta=225.6,243
XS Rating Curve= 0 ,0
Exp/Cntr=0.3,0.1

Type RM Length L Ch R = 1 ,11792.9 ,122.1,122.2,122.1
XS GIS Cut Line= 3
     2397816.114      337807.603     2397926.456      337510.195
     2397932.114      337411.315
#Sta/Elev= 30
       0     510       4  509.49    11.9  507.95    15.9  507.68    23.8  506.59
   42.75505.1231    63.4  504.32    79.3  503.21    91.2   502.1     119  500.33
   126.9   499.5   138.8  498.58   162.6  495.82   198.3   493.6     222  493.36
     234  492.51   241.9  491.51   245.8  491.02   249.8  490.87   253.8  491.08
   257.7  491.59   269.6  492.85   273.6  493.08   313.2  493.68     337  495.45
   348.9   496.8   376.6  499.16   404.4   501.3  411.76501.6617   416.3     502
#Mann= 5 ,-1 , 0
       0     .12       0   42.75     .06       0   241.9    .045       0
   257.7     .06       0  411.76     .12       0
Bank Sta=241.9,257.7
XS Rating Curve= 0 ,0
Exp/Cntr=0.3,0.1

Type RM Length L Ch R = 1 ,11670.7 ,248.5,227.1,203.5
XS GIS Cut Line= 3
     2397942.114      337813.771     2398052.456      337516.363
     2398058.114      337417.482
#Sta/Elev= 30
       0   504.2   22.44503.0182    39.6  501.51   47.74501.1309    75.3  500.16
   107.1  497.98   122.9  497.12   146.7  495.37   166.5  493.44   174.5  493.05
   190.3  491.82   210.2  491.69   222.1   491.2     234   490.6   237.9  490.74
   241.9  491.18   253.8  492.08   281.5  491.81   301.4  492.14   305.3  492.35
   313.2  492.91   321.2  493.62   325.1  494.18   333.1  494.79     337  495.51
   352.9  496.56   356.8  497.12   364.8   498.7   380.6  499.67   416.3  502.74
#Mann= 5 ,-1 , 0
       0     .06       0   22.44     .12       0   47.74     .06       0
   222.1    .045       0   241.9     .06       0
Bank Sta=222.1,241.9
XS Rating Curve= 0 ,0
Exp/Cntr=0.3,0.1

Type RM Length L Ch R = 1 ,11443.6 ,53.1,52.6,54.5
XS GIS Cut Line= 3
     2398412.562      337896.585     2398299.759      337724.939
     2398117.795      337436.537
#Sta/Elev= 30
       0   493.8    11.8  493.85    43.4  494.72    59.2  494.78    67.2  494.38
    98.8  493.82   110.6   493.9   122.4  493.19     154  491.93     162  491.09
   169.8  490.72   185.6  491.34   197.5  491.23  210.06490.8997     245   490.6
   268.8  489.96   288.7  490.21   304.5  489.62   312.5  489.42   320.4  489.58
   328.3  489.98   340.2  490.24  385.45490.3448   427.4  490.82   451.2  491.45
     483  492.56   498.8  493.32   510.7  493.71   534.5  495.03   546.4     496
#Mann= 5 ,-1 , 0
       0     .12       0  210.06    .016       0   304.5    .045       0
   320.4    .016       0  385.45     .12       0
#XS Ineff= 2 , 0
          189.26   491.9
Permanent Ineff=
       F       F
Bank Sta=304.5,320.4
XS Rating Curve= 0 ,0
Exp/Cntr=0.3,0.1

Type RM Length L Ch R = 1 ,11391   ,196.6,208.4,221
XS GIS Cut Line= 3
     2398441.408      337867.924     2398343.741      337705.623
       2398161.9      337416.552
#Sta/Elev= 30
       0  492.88    31.6  492.77    43.4     493    55.2  492.86    94.7  491.75
   110.5  491.69   138.1  490.75     150  491.08   153.9  490.79   181.5  490.42
   201.3  489.42   217.2  488.22   225.2  487.76   233.1  488.05   277.6  488.58
   288.7  488.56  306.72489.1477   320.5   489.2   328.4  488.72   340.3  488.73
   356.2  489.14   376.1  489.97  388.17491.3014   395.9  491.74   431.6  494.66
   471.4  495.77   491.2  495.82  502.04496.0828  515.48496.4044   530.9   496.8
#Mann= 8 ,-1 , 0
       0     .12       0   217.2    .045       0   233.1     .12       0
   277.6     .06       0  306.72     .12       0  388.17    .016       0
  502.04     .06       0  515.48    .016       0
#XS Ineff= 2 , 0
                          315.43          491.76
Permanent Ineff=
       F       F
Bank Sta=217.2,233.1
XS Rating Curve= 0 ,0
Exp/Cntr=0.3,0.1

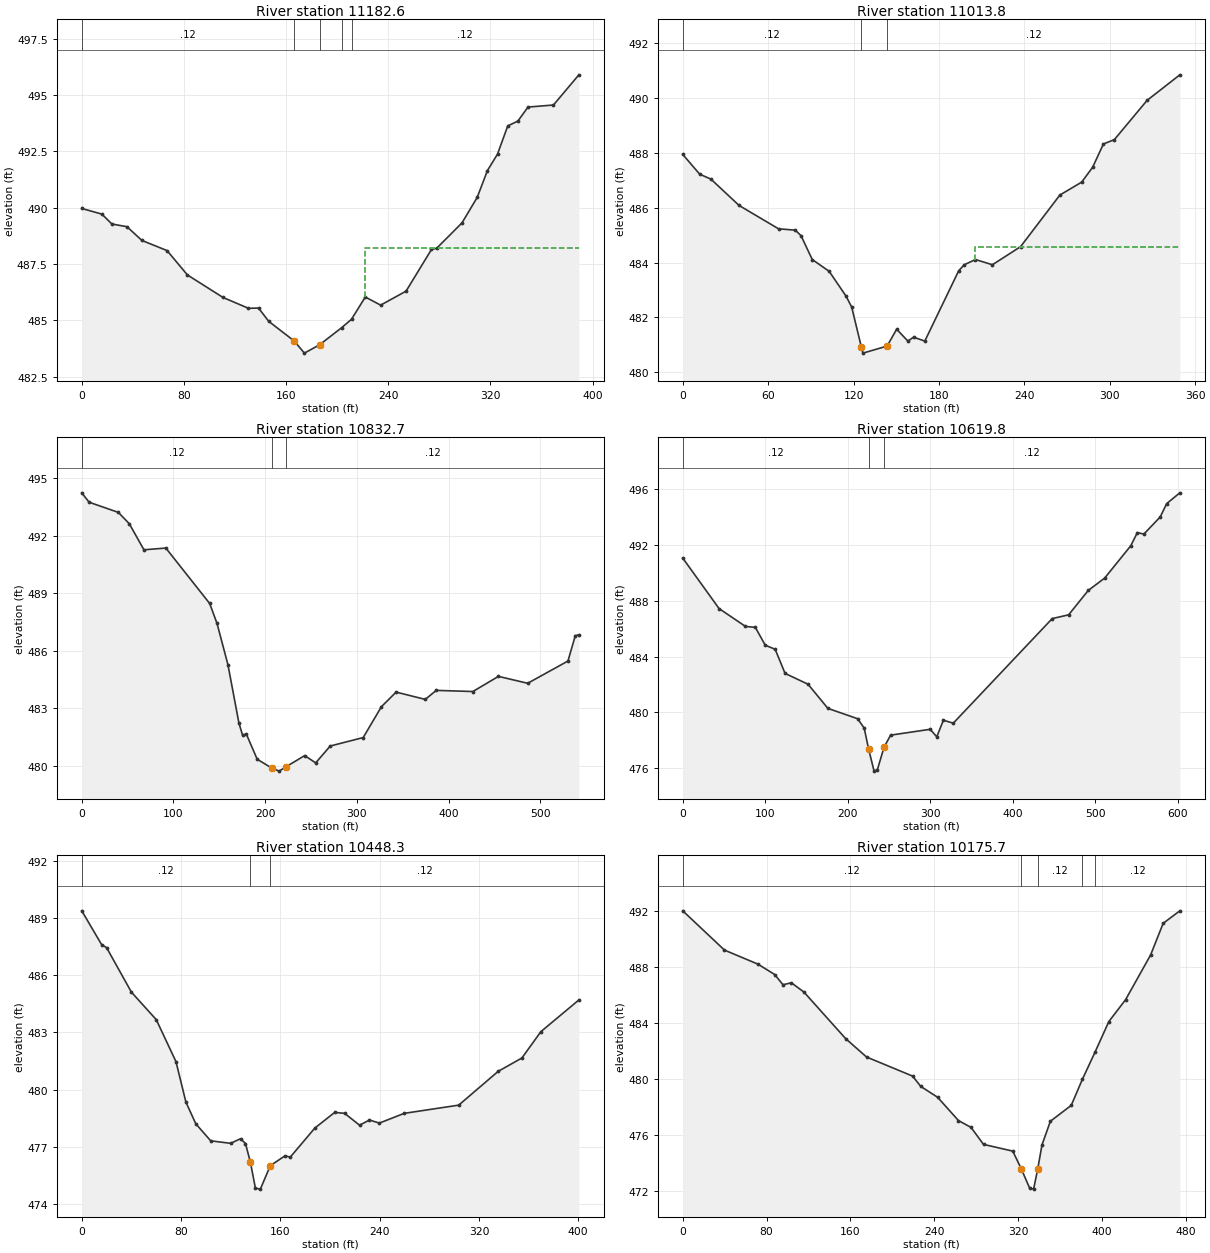
Type RM Length L Ch R = 1 ,11182.6 ,163.1,168.8,173.3
XS GIS Cut Line= 3
     2398465.693      337825.229     2398510.486      337775.704
     2398492.423      337453.749
#Sta/Elev= 30
       0  489.97    15.7  489.72    23.6  489.28    35.4  489.16    47.1  488.55
    66.8   488.1    82.7  487.02   110.6  486.02   130.5  485.54   138.4  485.55
   146.4  484.96   166.3  484.09   174.3  483.55   186.2  483.92  203.36484.6736
   211.2485.0533     222  486.04     234  485.68   253.9   486.3   273.8  488.15
   277.8   488.2   297.7  489.33   309.6  490.46   317.6  491.65   325.5  492.38
   333.5  493.63   341.5  493.85   349.4  494.47   369.3  494.56   389.2   495.9
#Mann= 5 ,-1 , 0
       0     .12       0   166.3    .045       0   186.2     .12       0
  203.36     .06       0   211.2     .12       0
#XS Ineff= 2 , 0
                          222.05           488.2
Permanent Ineff=
       F       F
Bank Sta=166.3,186.2
XS Rating Curve= 0 ,0
Exp/Cntr=0.3,0.1

Type RM Length L Ch R = 1 ,11013.8 ,178.9,181.1,183.1
XS GIS Cut Line= 3
     2398643.806      337836.544     2398685.337      337578.754
     2398655.826      337495.673
#Sta/Elev= 30
       0  487.94    11.9  487.22    19.8  487.04    39.6  486.08    67.3  485.23
    79.1  485.18    83.1  484.98      91  484.11   102.9  483.68   114.7  482.78
   118.7  482.38  125.47480.9288   126.6   480.7  143.62480.9581   150.3  481.57
   158.2  481.14   162.2  481.28   170.1  481.14   193.9   483.7   197.8  483.92
   205.7  484.11   217.6  483.92   237.4  484.58     265  486.46   280.3  486.93
     288  487.47   295.6  488.32   303.3  488.48   326.3  489.91   349.3  490.84
#Mann= 3 ,-1 , 0
       0     .12       0  125.47    .045       0  143.62     .12       0
#XS Ineff= 2 , 0
                          205.57          484.56
Permanent Ineff=
       F       F
Bank Sta=125.47,143.62
XS Rating Curve= 0 ,0
Exp/Cntr=0.3,0.1

Type RM Length L Ch R = 1 ,10832.7 ,202.2,212.9,223.5
XS GIS Cut Line= 3
     2398783.153      337966.018     2398881.389      337587.993
     2398811.514      337453.509
#Sta/Elev= 30
       0  494.24       8  493.75    39.9  493.22    51.8  492.63    67.8  491.27
    91.7  491.36   139.5  488.47   147.5  487.43   159.4  485.28   171.4  482.23
   175.4   481.6   179.4  481.67   191.3  480.35   207.2  479.89   215.2  479.73
   223.2  479.97   243.1  480.54   255.1  480.16     271  481.04   306.9  481.48
   326.8  483.09   342.8  483.85   374.6  483.47   386.6  483.94   426.5  483.88
   454.4  484.67   486.3  484.31   530.2  485.47   538.2  486.79   542.1  486.84
#Mann= 3 , 0 , 0
       0     .12       0   207.2    .045       0   223.2     .12       0
Bank Sta=207.2,223.2
XS Rating Curve= 0 ,0
Exp/Cntr=0.3,0.1

Type RM Length L Ch R = 1 ,10619.8 ,166.3,171.5,172.5
XS GIS Cut Line= 3
      2398878.46      338009.103     2399181.753      337668.851
     2399207.963      337524.529
#Sta/Elev= 30
       0  491.07      44  487.45      76  486.17      88   486.1     100  484.82
     112  484.53     124   482.8   151.9  482.02   175.9  480.29   211.9  479.55
   219.9  478.88  225.25  477.38   231.9  475.79   235.9  475.89   243.9  477.49
   251.9  478.37   299.9  478.79   307.9  478.25   315.9  479.44   327.9  479.23
   447.8  486.73   467.7     487   491.5  488.75   511.3  489.63     543  491.95
     551   492.9   558.9  492.79   578.7  494.02   586.6  494.98   602.5  495.75
#Mann= 3 , 0 , 0
       0     .12       0  225.25    .045       0   243.9     .12       0
Bank Sta=225.25,243.9
XS Rating Curve= 0 ,0
Exp/Cntr=0.3,0.1

Type RM Length L Ch R = 1 ,10448.3 ,261.7,272.5,280.3
XS GIS Cut Line= 3
     2399017.661      338056.794     2399258.864      337829.077
     2399326.359      337815.868
#Sta/Elev= 30
       0  489.37      16   487.6      20  487.44      40  485.11      60  483.67
    75.9  481.47    83.9  479.35    91.9  478.21   103.9  477.32   119.9  477.19
   127.9  477.43   131.9  477.18   135.9  476.19   139.9  474.84   143.9  474.79
   151.9  476.02   163.9  476.54   167.9  476.46   187.8  477.99   203.8  478.81
   211.8  478.76   223.8  478.14   231.8  478.41   239.8  478.25   259.8  478.76
   303.7  479.19   335.5  480.96   354.6  481.66   369.9  483.04   400.5   484.7
#Mann= 3 ,-1 , 0
       0     .12       0   135.9    .045       0   151.9     .12       0
Bank Sta=135.9,151.9
XS Rating Curve= 0 ,0
Exp/Cntr=0.3,0.1

Type RM Length L Ch R = 1 ,10175.7 ,158.6,162.5,165.6
XS GIS Cut Line= 2
     2399041.193      338247.459     2399459.312      338023.735
#Sta/Elev= 30
       0     492    39.8   489.2    71.7   488.2    87.7  487.46    95.6  486.73
   103.6  486.87   115.6  486.21   155.4  482.89   175.3  481.58   219.2  480.22
   227.1  479.48   243.1  478.71     263  477.05     275  476.56   286.9  475.35
   314.8  474.87   322.8  473.63   330.8  472.25   334.7  472.16   338.7  473.63
   342.7  475.31   350.7     477   370.6  478.13   381.2479.9845  393.22481.9144
   406.5  484.11   422.4  485.66   446.3  488.85   458.3  491.11   474.2     492
#Mann= 5 ,-1 , 0
       0     .12       0   322.8    .045       0   338.7     .12       0
   381.2     .06       0  393.22     .12       0
Bank Sta=322.8,338.7
XS Rating Curve= 0 ,0
Exp/Cntr=0.3,0.1

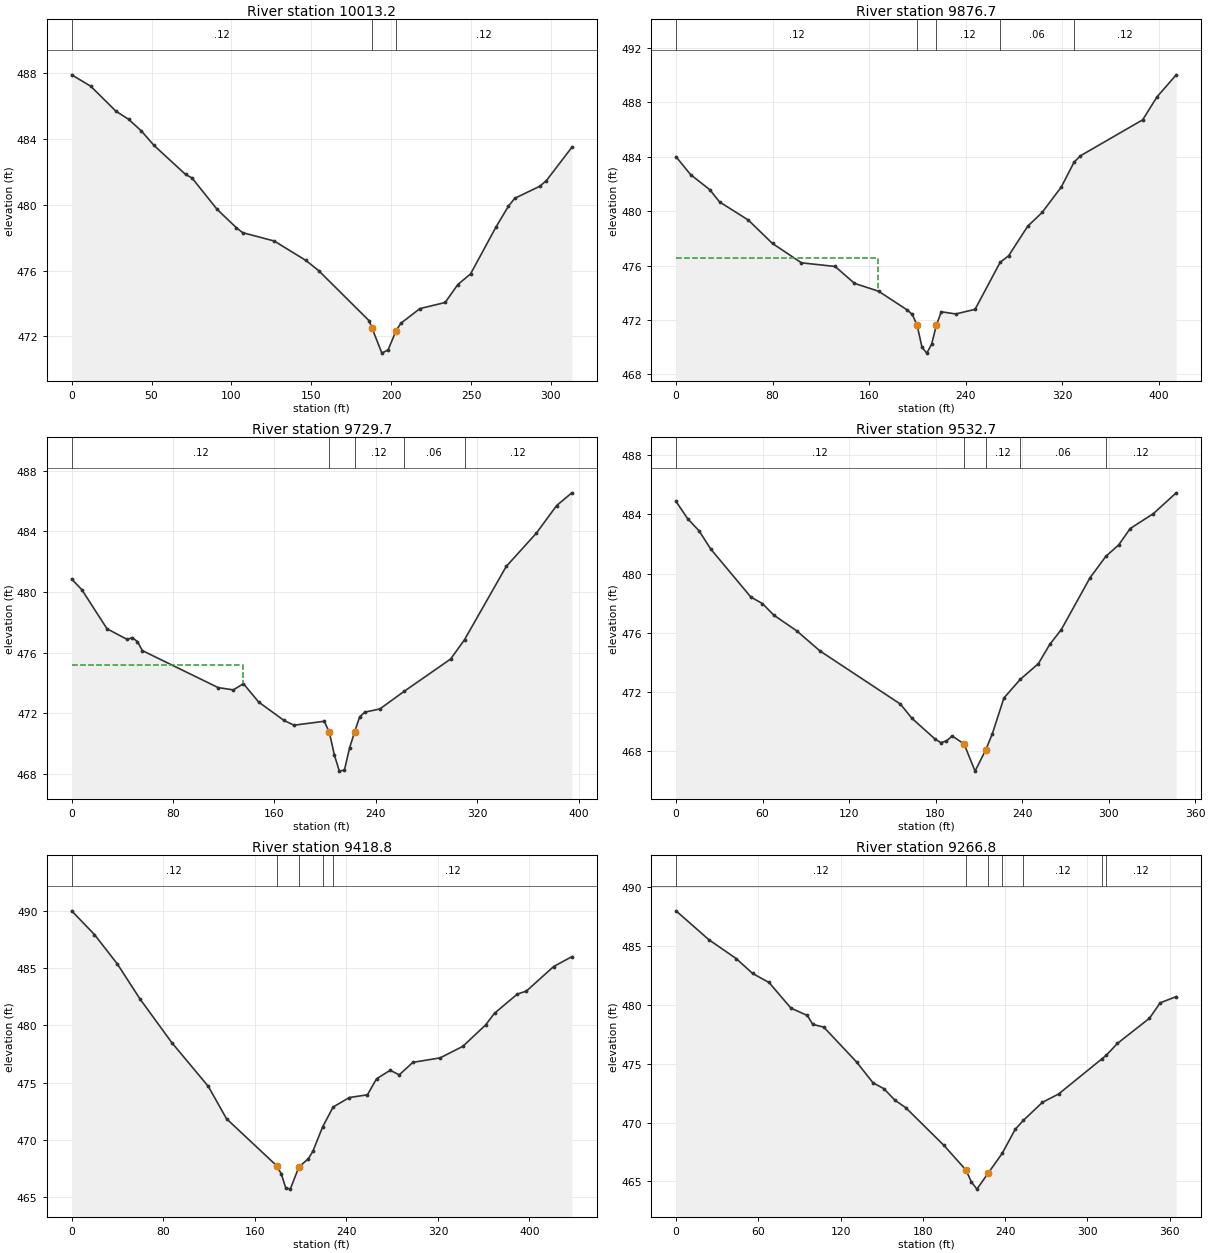
Type RM Length L Ch R = 1 ,10013.2 ,147.4,136.6,125.7
XS GIS Cut Line= 2
     2399167.551      338316.576     2399459.143      338202.643
#Sta/Elev= 30
       0  487.91    11.9  487.22    27.7   485.7    35.7   485.2    43.6   484.5
    51.5  483.62    71.3  481.85    75.3  481.64    91.1  479.72     103  478.62
     107  478.31   126.8   477.8   146.6  476.62   154.6     476   186.2  472.95
   188.1  472.48   194.2  470.98   198.1  471.18   203.1  472.35   206.1   472.8
     218  473.69   233.8  474.06   241.7  475.15   249.7   475.8   265.5  478.63
   273.4  479.92   277.4   480.4   293.2  481.14   297.2  481.48   313.1   483.5
#Mann= 3 ,-1 , 0
       0     .12       0   188.1    .045       0   203.1     .12       0
Bank Sta=188.1,203.1
XS Rating Curve= 0 ,0
Exp/Cntr=0.3,0.1

Type RM Length L Ch R = 1 ,9876.7  ,149.4,147,144.5
XS GIS Cut Line= 3
     2399291.679      338509.848     2399460.419      338317.803
     2399545.244      338183.715
#Sta/Elev= 30
       0     484      12  482.69      28  481.57      36  480.68    59.9  479.34
    79.9  477.62   103.9   476.2   131.8  475.93   147.8  474.69   167.8  474.11
   191.7  472.72   195.7   472.4   199.7  471.61   203.7     470   207.7  469.56
   211.7  470.22   215.7  471.63   219.7   472.6   231.7  472.44   247.7  472.78
  268.49476.2402   275.5  476.72   291.3  478.89   303.2   479.9   319.1  481.77
  329.68483.5958     335  484.07   386.5  486.71   398.4   488.4   414.3  490.02
#Mann= 5 ,-1 , 0
       0     .12       0   199.7    .045       0   215.7     .12       0
  268.49     .06       0  329.68     .12       0
#XS Ineff= 2 , 0
          167.61  476.55
Permanent Ineff=
       F       F
Bank Sta=199.7,215.7
XS Rating Curve= 0 ,0
Exp/Cntr=0.3,0.1

Type RM Length L Ch R = 1 ,9729.7  ,209.6,197,179.5
XS GIS Cut Line= 3
     2399428.895      338598.915     2399605.503      338347.906
     2399616.292       338260.94
#Sta/Elev= 30
       0  480.85       8  480.15    27.9  477.57    43.8  476.87    47.8  476.99
    51.8  476.73    55.8  476.13   115.6  473.69   127.6  473.54   135.5  473.95
   147.5  472.74   167.4  471.53   175.4  471.21   199.3  471.47   203.3  470.73
   207.3  469.23   211.2  468.18   215.2  468.25   219.2   469.7   223.2  470.76
   227.2  471.76   231.2  472.07   243.1  472.28  262.18473.4364   298.9  475.57
  309.95476.8528   342.8  481.68   366.7  483.89   382.6   485.7   394.6  486.54
#Mann= 5 ,-1 , 0
       0     .12       0   203.3    .045       0   223.2     .12       0
  262.18     .06       0  309.95     .12       0
#XS Ineff= 2 , 0
          134.99  475.19
Permanent Ineff=
       F       F
Bank Sta=203.3,223.2
XS Rating Curve= 0 ,0
Exp/Cntr=0.3,0.1

Type RM Length L Ch R = 1 ,9532.7  ,122.4,113.9,110.5
XS GIS Cut Line= 3
     2399783.188      338608.989     2399715.824      338519.774
     2399693.064      338285.776
#Sta/Elev= 30
       0  484.88       8  483.72      16  482.89      24  481.67    51.9  478.42
    59.9  477.98    67.9  477.19    83.8  476.13    99.8  474.78   155.6  471.19
   163.6  470.23   179.5  468.84   183.5  468.59   187.5  468.69   191.5  469.04
   199.8  468.49   207.4  466.66   214.8   468.1   219.4  469.19   227.4   471.6
   238.7 472.856   251.3  473.92   259.2  475.22   267.2  476.22   287.1  479.72
  298.12481.1722     307  481.94     315  483.05     331  484.05   346.9  485.46
#Mann= 5 ,-1 , 0
       0     .12       0   199.8    .045       0   214.8     .12       0
   238.7     .06       0  298.12     .12       0
Bank Sta=199.8,214.8
XS Rating Curve= 0 ,0
Exp/Cntr=0.3,0.1

Type RM Length L Ch R = 1 ,9418.8  ,156.6,152,146.3
XS GIS Cut Line= 3
     2399852.114      338614.302     2399810.835      338427.846
     2399768.114      338185.581
#Sta/Elev= 30
       0     490    19.9  487.93    39.8  485.38    59.7  482.31    87.5   478.5
   119.4  474.68   135.3  471.86     179  467.77     183  467.08     187  465.85
     191  465.72   198.5  467.65   206.8  468.37   210.8  469.04  219.28471.1545
  228.42472.8829   242.6  473.71   258.4  473.95   266.4  475.35   278.3  476.09
   286.2  475.69   298.1  476.78   321.9  477.17   341.8  478.18   361.6  480.04
   369.5  481.07   389.4  482.74   397.3     483   421.1  485.14     437     486
#Mann= 5 ,-1 , 0
       0     .12       0     179    .045       0   198.5     .12       0
  219.28     .06       0  228.42     .12       0
Bank Sta=179,198.5
XS Rating Curve= 0 ,0
Exp/Cntr=0.3,0.1

Type RM Length L Ch R = 1 ,9266.8  ,148.4,148.8,149
XS GIS Cut Line= 3
      2400053.25      338609.674     2399933.953      338370.537
     2399925.489      338273.456
#Sta/Elev= 30
       0     488    23.9  485.55    43.9  483.94    55.8  482.68    67.8  481.91
    83.8  479.73    95.7  479.11    99.7  478.35   107.7  478.12   131.6  475.16
   143.6  473.39   151.6  472.88   159.6  471.91   167.5  471.27   195.4  468.06
   211.4  465.97   215.4  464.95   219.4  464.35   227.4  465.68  237.76467.3797
   247.3  469.43   253.3   470.2   267.2  471.73   278.9  472.43  310.36475.4047
  313.71475.7225   321.8  476.73   345.2  478.87     353  480.18   364.7  480.71
#Mann= 7 ,-1 , 0
       0     .12       0   211.4    .045       0   227.4     .12       0
  237.76     .06       0   253.3     .12       0  310.36     .06       0
  313.71     .12       0
Bank Sta=211.4,227.4
XS Rating Curve= 0 ,0
Exp/Cntr=0.3,0.1

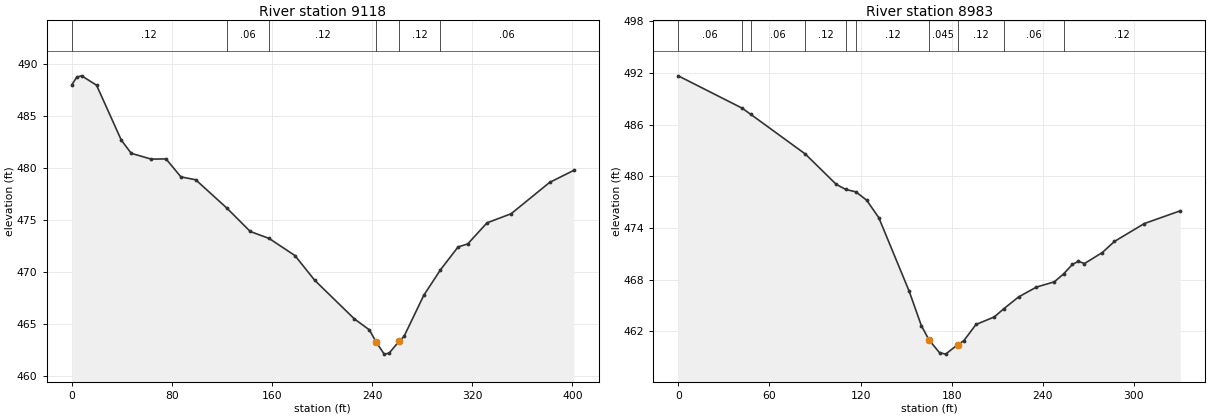
Type RM Length L Ch R = 1 ,9118    ,145.5,135,124.5
XS GIS Cut Line= 3
     2400189.678      338560.537     2400062.455      338296.446
     2399985.545      338220.621
#Sta/Elev= 30
       0     488       4  488.76     7.9  488.88    19.8  487.98    39.6  482.68
    47.5  481.42    63.4  480.86    75.3  480.88    87.2  479.15      99  478.87
  123.91 476.144   142.6  473.89  157.72473.2184   178.3  471.57   194.1  469.19
   225.8  465.47   237.7  464.42   243.4   463.2   249.6  462.08   253.5  462.17
   261.4  463.31   265.4  463.78   281.2  467.74  294.52470.1966   308.6   472.4
   316.3  472.69   331.7  474.72     351   475.6   381.8  478.62   401.1  479.78
#Mann= 6 ,-1 , 0
       0     .12       0  123.91     .06       0  157.72     .12       0
   243.4    .045       0   261.4     .12       0  294.52     .06       0
Bank Sta=243.4,261.4
XS Rating Curve= 0 ,0
Exp/Cntr=0.3,0.1

Type RM Length L Ch R = 1 ,8983    ,164,164.2,169.5
XS GIS Cut Line= 3
     2400319.606      338352.095       2400137.4      338221.824
     2400081.416      338131.236
#Sta/Elev= 30
       0  491.66      42 487.915   47.64487.2059   83.64482.5904     104  479.07
  110.18478.4856  116.94478.1948     124  477.24     132  475.21     152  466.68
     160  462.69   165.1  461.01     172  459.54     176  459.37     184  460.47
     188  460.93     196  462.81     208  463.68  214.24 464.624     224     466
   235.8  467.15   247.6  467.76  253.62468.6699   259.5  469.78   263.4  470.14
   267.4  469.88   279.2  471.16   287.1  472.44   306.8  474.52   330.5     476
#Mann= 10 ,-1 , 0
       0     .06       0      42     .08       0   47.64     .06       0
   83.64     .12       0  110.18     .06       0  116.94     .12       0
   165.1    .045       0     184     .12       0  214.24     .06       0
  253.62     .12       0
Bank Sta=165.1,184
XS Rating Curve= 0 ,0
Exp/Cntr=0.3,0.1