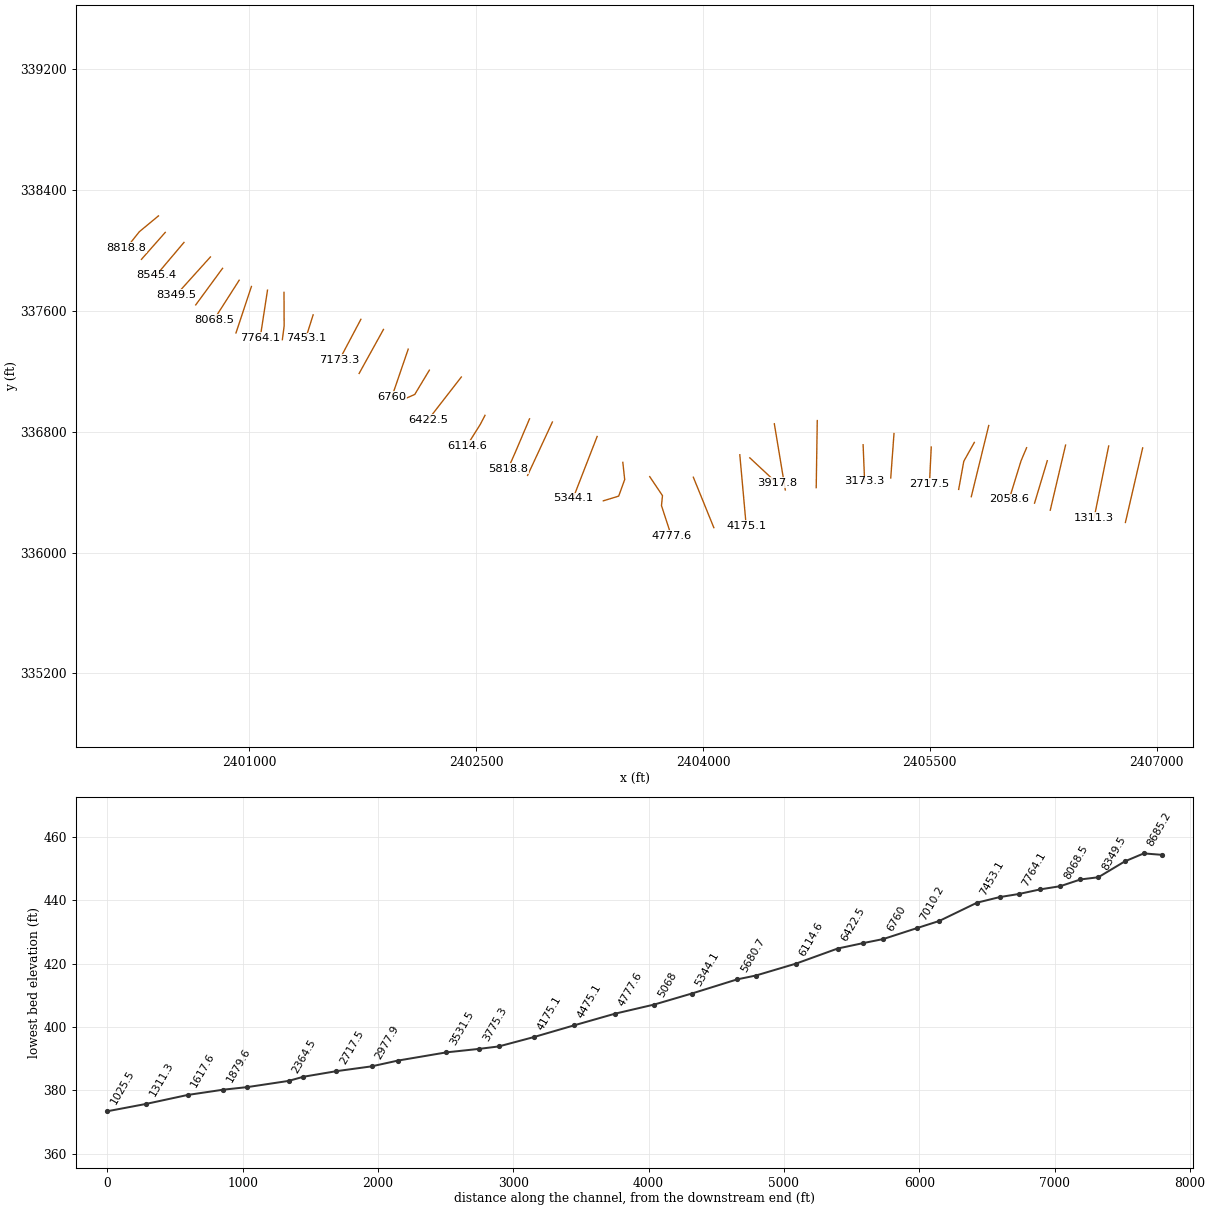
HEC-RAS study COLDSPRING.prj: COLDSPRING

--- COLDSPRING.g01 (geometry) --- (continued)

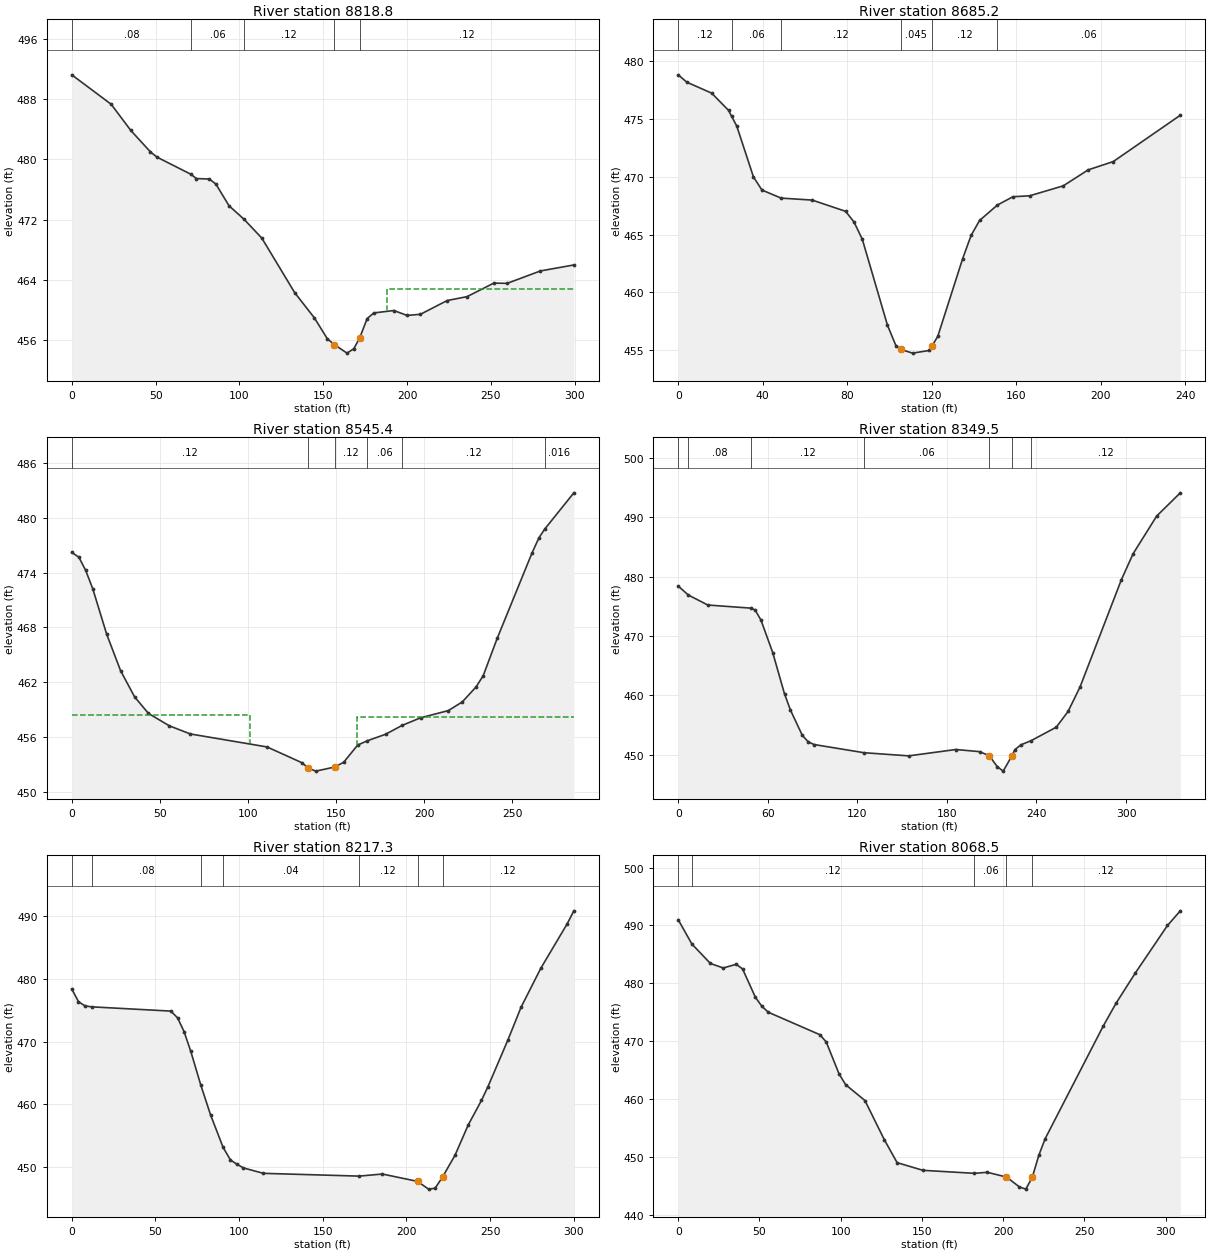
Type RM Length L Ch R = 1 ,8818.8  ,130,133.6,132
XS GIS Cut Line= 3
     2400399.022      338227.164     2400272.537      338122.391
     2400188.333      338016.537
#Sta/Elev= 30
       0  491.21    23.5  487.31    35.2  483.84    46.9     481    50.8   480.3
   71.04478.0284    74.3  477.46    82.1  477.39      86  476.72    93.8  473.85
  102.86472.0372   113.4  469.55     133  462.32   144.7  458.99   152.5   456.2
   156.7  455.43   164.2  454.31   168.2  454.89   171.7   456.3   176.2  458.89
   180.2  459.64   192.1  459.96     200  459.31     208  459.46   223.9  461.28
   235.8   461.8   251.8   463.6   259.7  463.56   279.6  465.21   299.5     466
#Mann= 5 ,-1 , 0
       0     .08       0   71.04     .06       0  102.86     .12       0
   156.7    .045       0   171.7     .12       0
#XS Ineff= 2 , 0
                          188.07          462.77
Permanent Ineff=
       F       F
Bank Sta=156.7,171.7
XS Rating Curve= 0 ,0
Exp/Cntr=0.3,0.1

Type RM Length L Ch R = 1 ,8685.2  ,139.3,139.8,140.3
XS GIS Cut Line= 2
     2400443.838       338117.78     2400286.548      337939.704
#Sta/Elev= 30
       0   478.8       4  478.17    15.8  477.22    23.8  475.73   25.21475.2383
    27.7  474.37    35.6  469.98    39.6  468.85   48.69468.1505    63.4  467.98
    79.2  467.01    83.2  466.08    87.1   464.6      99  457.18     103  455.41
   105.2  455.09   110.9  454.76   118.8  454.99   120.2  455.41   122.8   456.2
   134.6  462.92   138.6  464.93   142.6  466.22  151.06467.5547   158.4  468.27
   166.3  468.35   182.2  469.21     194  470.59   205.9  471.31   237.6  475.31
#Mann= 6 ,-1 , 0
       0     .12       0   25.21     .06       0   48.69     .12       0
   105.2    .045       0   120.2     .12       0  151.06     .06       0
Bank Sta=105.2,120.2
XS Rating Curve= 0 ,0
Exp/Cntr=0.3,0.1

Type RM Length L Ch R = 1 ,8545.4  ,196.6,195.9,195.2
XS GIS Cut Line= 2
      2400567.79      338051.608     2400383.843      337834.023
#Sta/Elev= 30
       0   476.2       4  475.69     7.9  474.23    11.9  472.23    19.8  467.25
    27.7  463.25    35.6   460.4    43.5  458.57    55.4  457.21    67.3  456.32
   110.8   454.9   130.6  453.17   134.2  452.58   138.5  452.25   149.2   452.7
   154.3  453.22   162.2   455.1  167.46455.5556   178.1  456.29  187.42457.2549
   197.9  458.09   213.7  458.88   221.6  459.83   229.5  461.49   233.5  462.72
   241.4  466.79   261.2  476.16   265.1  477.81  268.36478.7554   284.9  482.73
#Mann= 6 ,-1 , 0
       0     .12       0   134.2    .045       0   149.2     .12       0
  167.46     .06       0  187.42     .12       0  268.36    .016       0
#XS Ineff= 2 , 0
          101.24   458.4  161.61          458.16
Permanent Ineff=
       F       F
Bank Sta=134.2,149.2
XS Rating Curve= 0 ,0
Exp/Cntr=0.3,0.1

Type RM Length L Ch R = 1 ,8349.5  ,129.8,132.1,134.4
XS GIS Cut Line= 2
     2400742.477      337955.359     2400517.228      337705.437
#Sta/Elev= 30
       0  478.39    6.81476.8845    19.8  475.21   48.65474.6835    51.5  474.37
    55.4  472.69    63.3  467.21    71.2  460.26    75.2  457.51    83.1  453.28
    87.1  452.17      91  451.72   124.4 450.342   154.4  449.81     186  450.88
   201.9  450.52   208.4  449.84   213.7  448.01   217.7  447.24   223.4  449.73
   225.6  450.86   229.6  451.67  236.49452.3768   253.3  454.64   261.2  457.29
   269.2   461.4   296.9  479.46   304.8  483.86   320.6   490.2   336.4   494.1
#Mann= 7 ,-1 , 0
       0     .12       0    6.81     .08       0   48.65     .12       0
   124.4     .06       0   208.4    .045       0   223.4     .06       0
  236.49     .12       0
Bank Sta=208.4,223.4
XS Rating Curve= 0 ,0
Exp/Cntr=0.3,0.1

Type RM Length L Ch R = 1 ,8217.3  ,147.4,148.8,150.3
XS GIS Cut Line= 2
     2400822.892      337880.321     2400645.506      337638.329
#Sta/Elev= 30
       0  478.36       4  476.35     7.9  475.66   12.07475.5153    59.2  474.84
    63.2  473.78    67.1  471.58    71.1  468.45    77.1463.0782    82.9  458.36
   90.46453.1593    94.8  451.19    98.7  450.49   102.6  449.91   114.5  449.05
  171.62448.6093   185.6  448.94   206.6  447.77   213.2  446.54   217.1  446.68
   221.6  448.49     229  451.93   236.9  456.75   244.8  460.64   248.7  462.84
   260.6  470.25   268.5  475.48   280.3  481.67   296.1  488.75     300  490.78
#Mann= 7 ,-1 , 0
       0     .12       0   12.07     .08       0    77.1     .12       0
   90.46     .04       0  171.62     .12       0   206.6    .045       0
   221.6     .12       0
Bank Sta=206.6,221.6
XS Rating Curve= 0 ,0
Exp/Cntr=0.3,0.1

Type RM Length L Ch R = 1 ,8068.5  ,144.5,149.8,154.9
XS GIS Cut Line= 2
     2400932.757       337801.35     2400766.366      337540.958
#Sta/Elev= 30
       0  490.99     8.4486.7913    19.8  483.43    27.7  482.65    35.7  483.29
    39.6  482.48    47.5  477.58    51.5  476.01    55.5  474.99    87.2  471.11
    91.1  469.85      99  464.33     103  462.48   114.9  459.74   126.8  452.98
   134.7     449   150.6  447.67  182.29447.1529   190.2  447.33     202  446.51
     210   444.8   213.9  444.42   217.9  446.47   221.9  450.25   225.8  453.13
   261.5  472.58   269.4  476.53   281.3  481.78   301.1     490     309  492.53
#Mann= 5 ,-1 , 0
       0     .06       0     8.4     .12       0  182.29     .06       0
     202    .045       0   217.9     .12       0
Bank Sta=202,217.9
XS Rating Curve= 0 ,0
Exp/Cntr=0.3,0.1

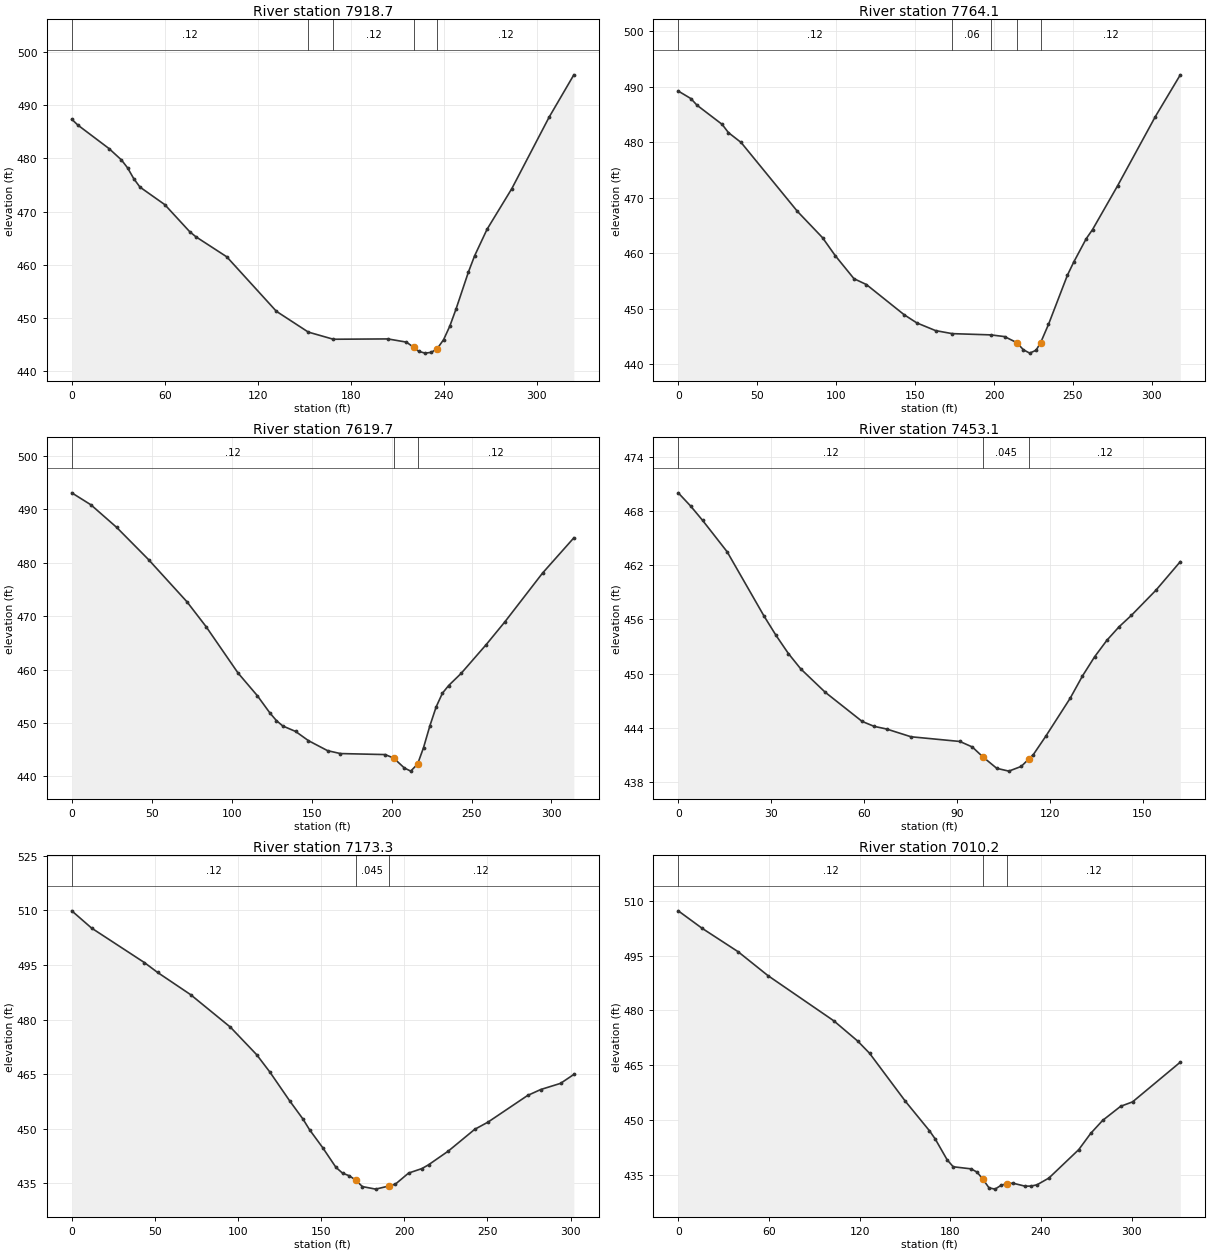
Type RM Length L Ch R = 1 ,7918.7  ,151.2,154.6,157.6
XS GIS Cut Line= 2
     2401013.701      337760.155     2400911.673      337452.752
#Sta/Elev= 30
       0  487.35       4  486.24      24  481.85      32  479.72      36  478.22
      40  476.18      44   474.6      60  471.31      76  466.25      80  465.28
     100   461.5     132  451.26  152.59447.3536  168.74 446.009   203.9  446.07
   215.9  445.47   220.7  444.46   223.9  443.73   227.9   443.4   231.9  443.54
   235.7  444.22   239.9  445.94   243.9  448.49   247.9  451.69   255.9  458.65
   259.9   461.7   267.9  466.67   283.9  474.32   307.9  487.72   323.9   495.7
#Mann= 5 ,-1 , 0
       0     .12       0  152.59     .06       0  168.74     .12       0
   220.7    .045       0   235.7     .12       0
Bank Sta=220.7,235.7
XS Rating Curve= 0 ,0
Exp/Cntr=0.3,0.1

Type RM Length L Ch R = 1 ,7764.1  ,140.6,144.4,147.5
XS GIS Cut Line= 2
     2401120.083      337735.921     2401071.761      337421.602
#Sta/Elev= 30
       0  489.22       8  487.86    11.9  486.66    27.8  483.21    31.8  481.72
    39.8  479.95    75.5  467.52    91.4  462.78    99.4  459.56   111.3  455.39
   119.2  454.33   143.1  448.89   151.1  447.42     163  446.03  173.53 445.484
  198.01 445.258   206.7  444.95   214.5  443.85   218.6  442.58   222.6  441.97
   226.6  442.48   229.5  443.84   234.5  447.14   246.5  456.02   250.4  458.33
   258.4   462.6   262.4  464.24   278.3  472.15   302.1  484.57     318  492.14
#Mann= 5 ,-1 , 0
       0     .12       0  173.53     .06       0  198.01     .12       0
   214.5    .045       0   229.5     .12       0
Bank Sta=214.5,229.5
XS Rating Curve= 0 ,0
Exp/Cntr=0.3,0.1

Type RM Length L Ch R = 1 ,7619.7  ,173.6,166.6,160.5
XS GIS Cut Line= 3
     2401229.218      337721.192      2401230.05      337497.241
     2401218.237      337408.024
#Sta/Elev= 30
       0  493.09      12  490.84      28  486.64      48  480.59      72   472.7
      84  468.03     104  459.34     116  455.12     124  451.83     128  450.43
     132  449.42     140   448.4     148  446.68     160   444.8     168  444.26
     196  444.07   201.3  443.42     208  441.56     212  440.97   216.3  442.31
     220  445.38     224  449.49   227.9  453.01   231.8  455.56   235.7     457
   243.5  459.27   259.2  464.67   270.9  468.94   294.4  478.05     314  484.66
#Mann= 3 ,-1 , 0
       0     .12       0   201.3    .045       0   216.3     .12       0
Bank Sta=201.3,216.3
XS Rating Curve= 0 ,0
Exp/Cntr=0.3,0.1

Type RM Length L Ch R = 1 ,7453.1  ,283.8,279.8,275.7
XS GIS Cut Line= 2
     2401421.892      337572.389      2401372.89      337417.753
#Sta/Elev= 30
       0     470       4  468.54     7.9  466.94    15.8  463.48    27.7  456.38
    31.6  454.23    35.6  452.22    39.6  450.52    47.5  447.94    59.4  444.72
    63.3  444.17    67.3  443.88    75.2  443.02      91   442.5      95  441.89
    98.4   440.8   102.9  439.53   106.8  439.22   110.8  439.74   113.4  440.61
   114.7  441.04   118.7  443.06   126.6  447.27   130.6  449.75   134.5  451.86
   138.5   453.7   142.4  455.18   146.4  456.45   154.3  459.22   162.2  462.39
#Mann= 3 ,-1 , 0
       0     .12       0    98.4    .045       0   113.4     .12       0
Bank Sta=98.4,113.4
XS Rating Curve= 0 ,0
Exp/Cntr=0.3,0.1

Type RM Length L Ch R = 1 ,7173.3  ,162.8,163.1,162.8
XS GIS Cut Line= 2
     2401737.669      337543.105     2401596.349      337276.245
#Sta/Elev= 30
       0  509.85    11.9  505.12    43.7  495.64    51.6  492.94    71.5  486.83
    95.4  477.92   111.2  470.36   119.2  465.56   131.1  457.66   139.1  452.66
     143  449.77     151  444.78   158.9  439.42   162.9  437.82   166.9  437.11
   170.8  435.92   174.8  434.14   182.8  433.44   190.7  434.29   194.7  434.82
   202.6  437.85   210.6  439.08   214.6  440.12   226.5  443.89   242.4  449.87
   250.3  451.82   274.2  459.16   282.1  460.79     294  462.48     302  464.93
#Mann= 3 ,-1 , 0
       0     .12       0   170.8    .045       0   190.7     .12       0
Bank Sta=170.8,190.7
XS Rating Curve= 0 ,0
Exp/Cntr=0.3,0.1

Type RM Length L Ch R = 1 ,7010.2  ,246.9,250.2,254.1
XS GIS Cut Line= 2
     2401886.773      337475.671     2401725.982      337184.812
#Sta/Elev= 30
       0  507.22    15.8  502.45    39.6  496.06    59.4  489.52   102.9   477.2
   118.7  471.68   126.6  468.33   150.4  455.17   166.2  447.19   170.1   444.9
     178   439.2     182  437.32   193.9  436.74   197.8  435.84   201.8  433.84
   205.7  431.55   209.7  431.21   213.6  432.24   217.6  432.72   221.6  432.83
   229.5  432.02   233.4  432.04   237.4  432.38   245.3  434.23   265.1  442.01
     273  446.44   280.9  449.98   292.8  453.83   300.7  455.04   332.3  465.89
#Mann= 3 ,-1 , 0
       0     .12       0   201.8    .045       0   217.6     .12       0
Bank Sta=201.8,217.6
XS Rating Curve= 0 ,0
Exp/Cntr=0.3,0.1

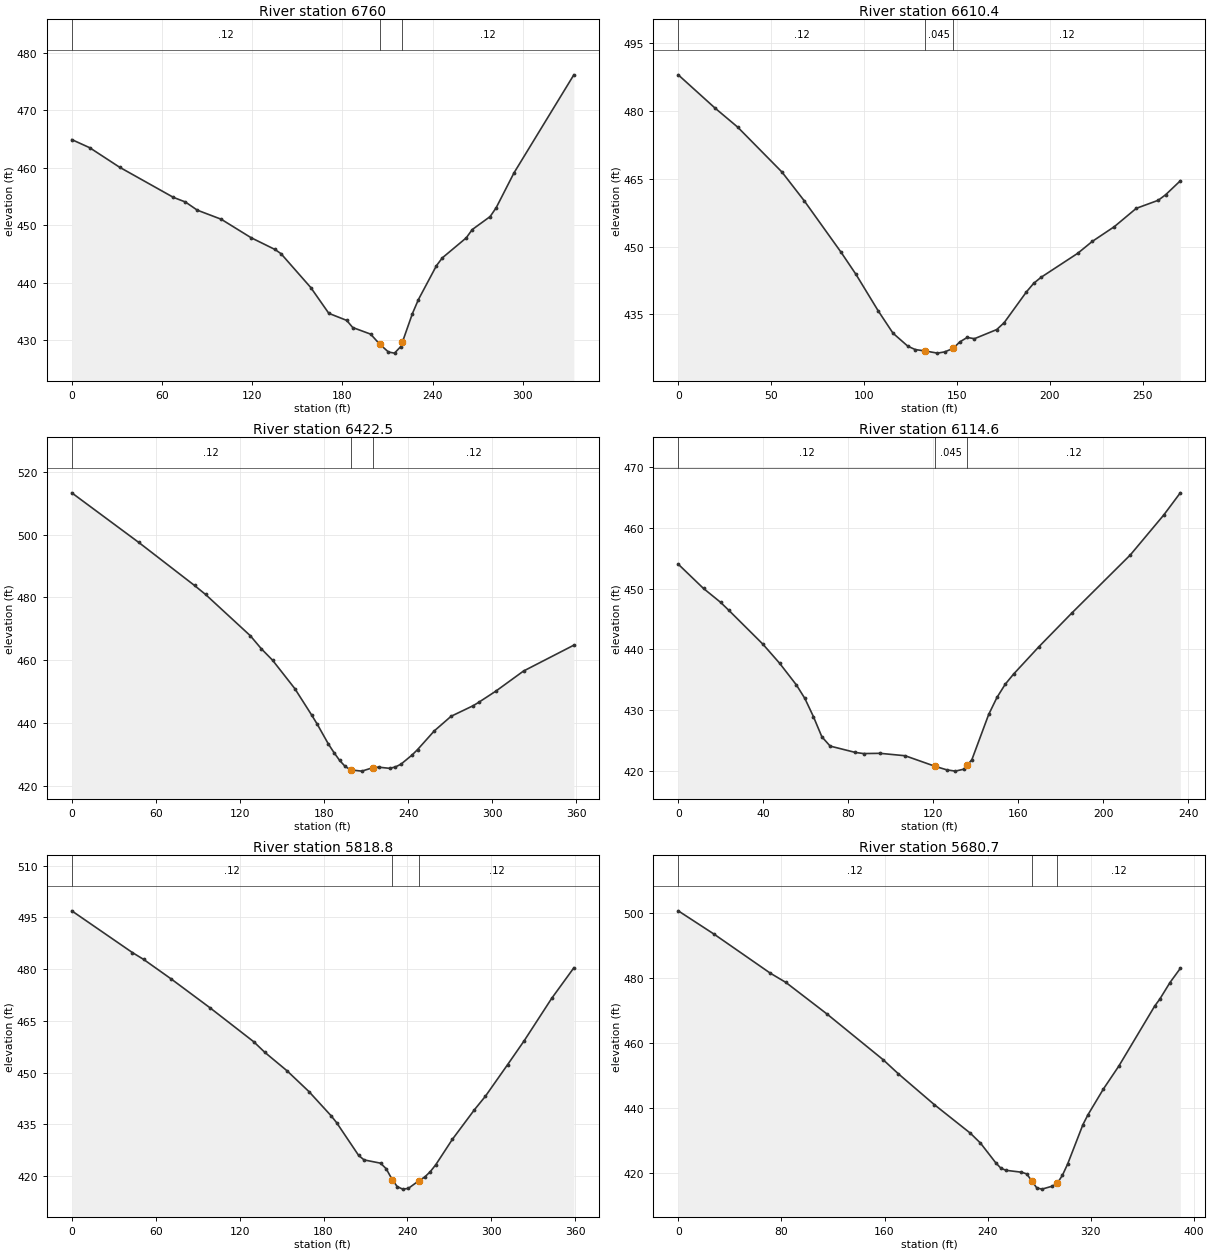
Type RM Length L Ch R = 1 ,6760    ,155.7,149.6,143.3
XS GIS Cut Line= 2
     2402050.519      337345.514     2401942.281      337029.528
#Sta/Elev= 30
       0  464.93    11.9  463.52    31.8  460.12    67.6  454.87    75.6  454.06
    83.5  452.64    99.4  451.06   119.3  447.84   135.2  445.79   139.2  445.06
     159  439.16     171  434.67   182.9  433.44   186.9   432.2   198.8  431.05
     205  429.26   210.7  427.93   214.7  427.74   218.7  428.84     220  429.69
   226.6  434.62   230.6  437.07   242.6  442.97   246.5  444.33   262.4  447.81
   266.4  449.26   278.3  451.52   282.3  453.05   294.2  459.14     334  476.21
#Mann= 3 ,-1 , 0
       0     .12       0     205    .045       0     220     .12       0
Bank Sta=205,220
XS Rating Curve= 0 ,0
Exp/Cntr=0.3,0.1

Type RM Length L Ch R = 1 ,6610.4  ,189.3,187.9,186.4
XS GIS Cut Line= 3
      2402190.26       337206.39     2402093.813      337045.772
     2402017.968      337012.491
#Sta/Elev= 30
       0     488    19.9  480.61    31.9  476.47    55.8  466.51    67.8  460.15
    87.7  448.72    95.7  443.84   107.6  435.81   115.6  430.85   123.6  427.97
   127.6  427.23     133  426.92   139.5  426.45   143.5  426.73     148  427.52
   151.5  428.92   155.5  429.92   159.4  429.64   171.4  431.66   175.4  433.18
   187.4     440   191.3  441.89   195.2   443.2     215  448.53   222.8  451.15
   234.7  454.42   246.5  458.47   258.3  460.25   262.3  461.48   270.2  464.56
#Mann= 3 ,-1 , 0
       0     .12       0     133    .045       0     148     .12       0
Bank Sta=133,148
XS Rating Curve= 0 ,0
Exp/Cntr=0.3,0.1

Type RM Length L Ch R = 1 ,6422.5  ,305.8,307.9,309.9
XS GIS Cut Line= 2
     2402401.769      337161.209     2402182.078      336878.216
#Sta/Elev= 30
       0  513.29    47.8  497.51    87.6  483.81    95.5  480.94   127.4  467.83
   135.3  463.66   143.3  460.03   159.2  450.98   171.2  442.58   175.2  439.66
   183.1  433.39   187.1  430.66   191.1  428.18     195  426.28     199  425.12
     207  424.74     215  425.86   218.9     426   226.9  425.63   230.9  426.06
   234.9  426.94   242.8  429.85   246.8  431.61   258.7  437.54   270.7  442.19
   286.6  445.59   290.6  446.69   302.5  450.15   322.4  456.59   358.3  464.82
#Mann= 3 ,-1 , 0
       0     .12       0     199    .045       0     215     .12       0
Bank Sta=199,215
XS Rating Curve= 0 ,0
Exp/Cntr=0.3,0.1

Type RM Length L Ch R = 1 ,6114.6  ,292.2,295.8,299.1
XS GIS Cut Line= 3
      2402558.38      336907.682     2402527.217      336847.721
     2402437.342      336704.901
#Sta/Elev= 30
       0  454.04    11.9  450.04    19.9  447.77    23.8  446.45    39.8  440.89
    47.7  437.74    55.6  434.17    59.6  431.94    63.6  428.97    67.6  425.63
    71.5   424.1    83.3  423.06    87.2  422.87      95  422.91   106.8  422.51
   120.9  420.77   126.4  420.19   130.4  419.98   134.3  420.29   135.9  420.93
   138.2  421.86   146.1   429.3     150   432.1   153.9  434.28   157.8  435.94
   169.6   440.4   185.3  446.02   212.8  455.57   228.5  462.13   236.3  465.78
#Mann= 3 ,-1 , 0
       0     .12       0   120.9    .045       0   135.9     .12       0
Bank Sta=120.9,135.9
XS Rating Curve= 0 ,0
Exp/Cntr=0.3,0.1

Type RM Length L Ch R = 1 ,5818.8  ,138.8,138.1,137.6
XS GIS Cut Line= 3
      2402852.88      336884.575     2402760.327       336666.82
     2402711.009      336554.795
#Sta/Elev= 30
       0  496.89    43.4  484.78    51.3  482.83      71  477.17    98.6  468.86
   130.1  458.95     138  455.89   153.8  450.57   169.6   444.5   185.3  437.55
   189.3  435.54   205.1  426.01     209   424.7   220.8  423.75   224.8  422.15
   229.1  419.01   232.7  416.97   236.6  416.23   240.6  416.43   248.4  418.72
   252.4  419.74   256.4  421.32   260.3  423.32   272.1  430.64   287.9  439.23
   295.8  443.17   311.6  452.29   323.5  459.24   343.2  471.55     359  480.37
#Mann= 3 ,-1 , 0
       0     .12       0   229.1    .045       0   248.4     .12       0
Bank Sta=229.1,248.4
XS Rating Curve= 0 ,0
Exp/Cntr=0.3,0.1

Type RM Length L Ch R = 1 ,5680.7  ,335,336.5,337.9
XS GIS Cut Line= 2
     2403003.885      336863.531     2402839.926      336510.382
#Sta/Elev= 30
       0   500.7    27.8  493.52    71.5  481.48    83.4  478.68   115.2  468.99
   158.9  454.87   170.8   450.5   198.6  441.04   226.5  432.26   234.4   429.2
   246.3  423.11   250.3  421.44   254.3  420.81   266.2  420.23   270.2  419.72
   274.1  417.63   278.1  415.38   282.1  415.02     290  415.92     294  416.83
     298  419.31     302  422.74   313.9  434.91   317.8  437.93   329.8  445.88
   341.7   452.9   369.5  471.36   373.5  473.53   381.4  478.63   389.4  482.99
#Mann= 3 ,-1 , 0
       0     .12       0   274.1    .045       0     294     .12       0
Bank Sta=274.1,294
XS Rating Curve= 0 ,0
Exp/Cntr=0.3,0.1

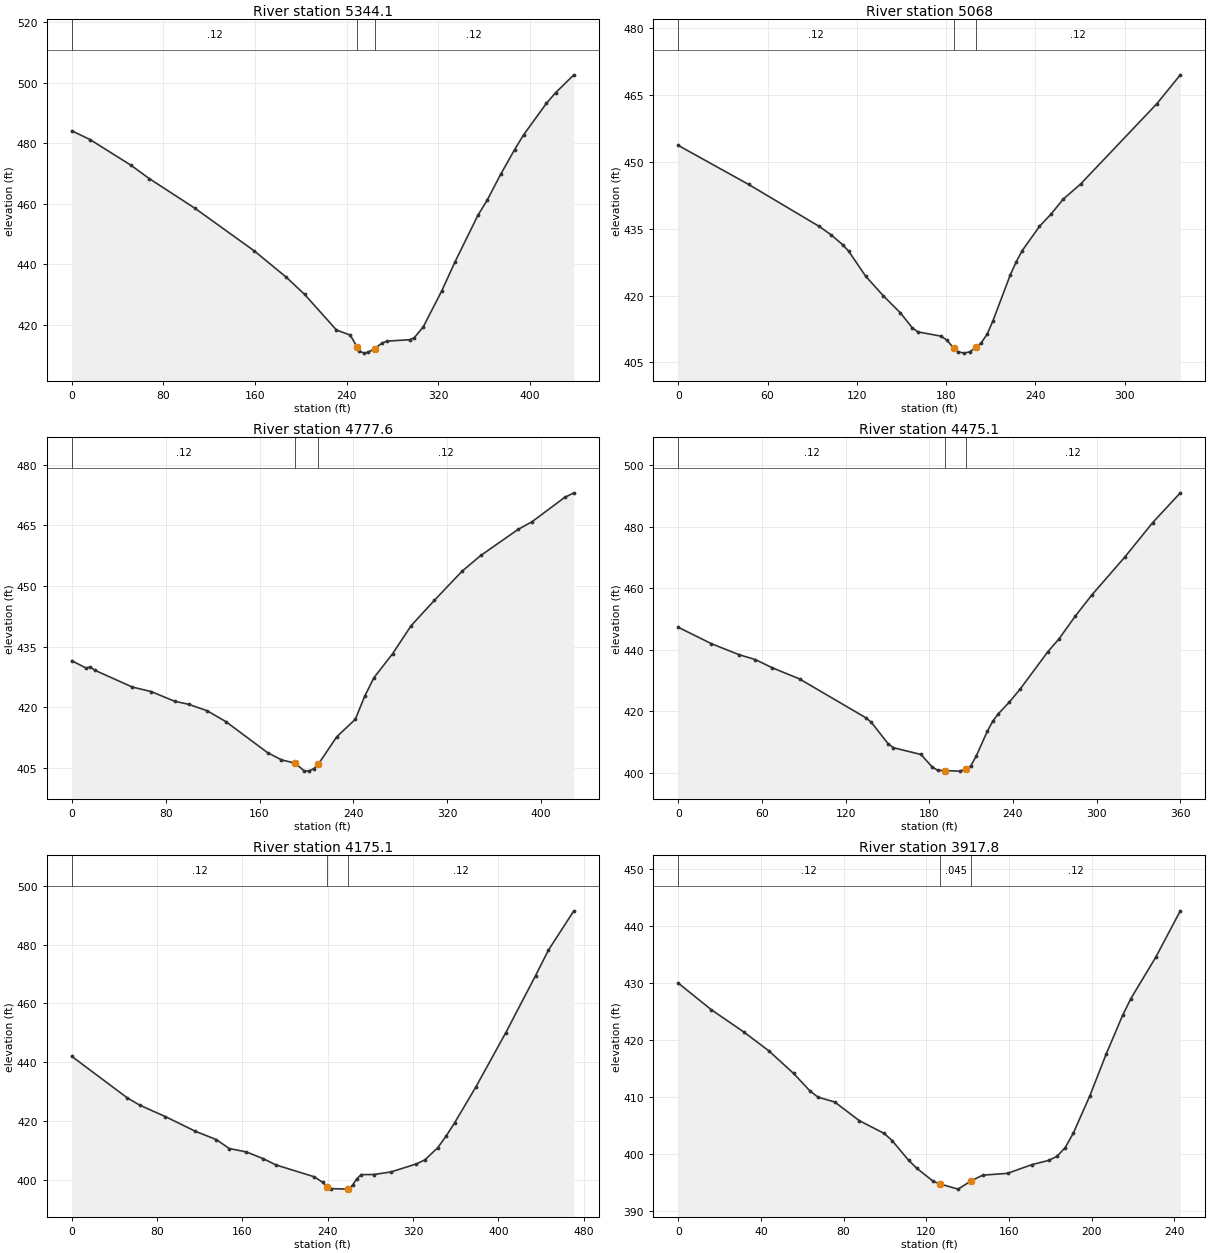
Type RM Length L Ch R = 1 ,5344.1  ,275.6,276.1,276.6
XS GIS Cut Line= 2
     2403299.812      336767.726     2403140.964      336359.196
#Sta/Elev= 30
       0  484.04    15.9  481.17    51.8  472.64    67.7  468.24   107.6  458.42
   159.4  444.32   187.3  435.63   203.2  429.98   231.1  418.18   243.1  416.51
   249.3  412.43     251  411.26     255  410.54     259  410.87   264.3  412.02
     271  413.89     275   414.5   294.9  414.97   298.9  415.59   306.8   419.2
   322.8  430.99   334.7  440.83   354.6  456.15   362.6   461.1   374.6   469.8
   386.5  477.78   394.5  482.75   414.4  493.17   422.4  496.65   438.3  502.56
#Mann= 3 ,-1 , 0
       0     .12       0   249.3    .045       0   264.3     .12       0
Bank Sta=249.3,264.3
XS Rating Curve= 0 ,0
Exp/Cntr=0.3,0.1

Type RM Length L Ch R = 1 ,5068    ,284.8,290.4,299.9
XS GIS Cut Line= 4
     2403469.661      336596.562     2403482.072      336482.836
      2403442.43      336373.319     2403340.687      336342.093
#Sta/Elev= 30
       0   453.7    47.3  444.93    94.7  435.52   102.6  433.65   110.5   431.4
   114.4     430     126  424.31   137.7  419.97   149.3   416.1   157.1  412.82
     161  411.85   176.5  410.89   180.4  410.02   185.2  408.14   188.2  407.36
     192  407.08   195.9  407.38   200.2  408.38   203.7  409.45   207.6  411.38
   211.5  414.39   223.1  424.67     227  427.51   230.9     430   242.7  435.53
   250.6  438.33   258.5  441.59   270.3  445.02   321.5  463.03   337.3  469.53
#Mann= 3 ,-1 , 0
       0     .12       0   185.2    .045       0   200.2     .12       0
Bank Sta=185.2,200.2
XS Rating Curve= 0 ,0
Exp/Cntr=0.3,0.1

Type RM Length L Ch R = 1 ,4777.6  ,291.8,302.5,309.2
XS GIS Cut Line= 4
      2403647.62      336502.049     2403731.918      336376.479
     2403725.293      336310.137     2403790.522      336110.565
#Sta/Elev= 30
       0  431.49    11.9  429.72    15.9  429.91    19.9   429.1    51.7  424.97
    67.7  423.86    87.6  421.47    99.5  420.72   115.4  419.12   131.3  416.44
   166.9  408.75   178.7  406.98   190.5  406.14   198.3  404.19   202.2  404.24
   206.2  404.79   210.1  405.89   225.8  412.67   241.7  417.03   249.6  422.68
   257.5  427.28   273.4  433.21   289.2  440.14     309  446.41   332.8  453.67
   348.6  457.51   380.3  463.94   392.2  465.84     420  471.85   427.9     473
#Mann= 3 ,-1 , 0
       0     .12       0   190.5    .045       0   210.1     .12       0
Bank Sta=190.5,210.1
XS Rating Curve= 0 ,0
Exp/Cntr=0.3,0.1

Type RM Length L Ch R = 1 ,4475.1  ,305.9,300,294
XS GIS Cut Line= 2
     2403936.077      336498.226     2404071.464      336164.537
#Sta/Elev= 30
       0   447.3    23.7  441.98    43.5   438.4    55.4  436.78    67.3  434.15
    87.1  430.47   134.6  417.85   138.5  416.39   150.4  409.49   154.3  408.13
   174.1  405.92     182  401.93     186   400.8   191.6  400.66   201.8  400.51
   206.6  401.19   209.7  402.14   213.7  405.39   221.6   413.4   225.6  416.77
   229.5  419.11   237.4  422.92   245.4   427.3   265.1  439.34     273  443.47
   284.9     451   296.8  457.89   320.5  470.24   340.3  481.35   360.1  491.02
#Mann= 3 ,-1 , 0
       0     .12       0   191.6    .045       0   206.6     .12       0
Bank Sta=191.6,206.6
XS Rating Curve= 0 ,0
Exp/Cntr=0.3,0.1

Type RM Length L Ch R = 1 ,4175.1  ,241.6,257.3,273.8
XS GIS Cut Line= 2
     2404243.261      336647.007     2404285.437      336178.191
#Sta/Elev= 30
       0     442    51.9   427.9    63.8  425.36    87.8  421.48   115.7  416.51
   135.6  413.64   147.6  410.61   163.6  409.46   179.5  407.16   191.5  405.01
   227.4  400.98   235.4  399.04   239.5  397.64   243.3  396.95   259.3  396.78
   263.3  398.18   267.3  400.32   271.3  401.72   283.2  401.76   299.2  402.63
   323.1  405.36   331.1  406.77   343.1  410.89     351  414.88     359  419.41
     379  431.68   406.9  450.07   434.8  469.49   446.8  478.13   470.7  491.56
#Mann= 3 ,-1 , 0
       0     .12       0   239.5    .045       0   259.3     .12       0
Bank Sta=239.5,259.3
XS Rating Curve= 0 ,0
Exp/Cntr=0.3,0.1

Type RM Length L Ch R = 1 ,3917.8  ,156,142.5,127.5
XS GIS Cut Line= 2
     2404309.352      336626.525      2404486.98       336460.85
#Sta/Elev= 30
       0     430    15.9  425.35    31.9  421.37    43.8  418.12    55.8  414.15
    63.7  411.09    67.7  409.97    75.7  409.14    87.6  405.86    99.6  403.63
   103.5  402.36   111.5  398.89   115.5  397.49   123.4  395.21   126.7  394.75
   135.4  393.85   141.7   395.3   147.3   396.3   159.3  396.62   171.2  398.16
   179.2  398.89   183.2   399.6   187.2  401.13   191.1  403.65   199.1   410.2
   207.1   417.6     215  424.35     219  427.29     231  434.52   242.9  442.67
#Mann= 3 ,-1 , 0
       0     .12       0   126.7    .045       0   141.7     .12       0
Bank Sta=126.7,141.7
XS Rating Curve= 0 ,0
Exp/Cntr=0.3,0.1

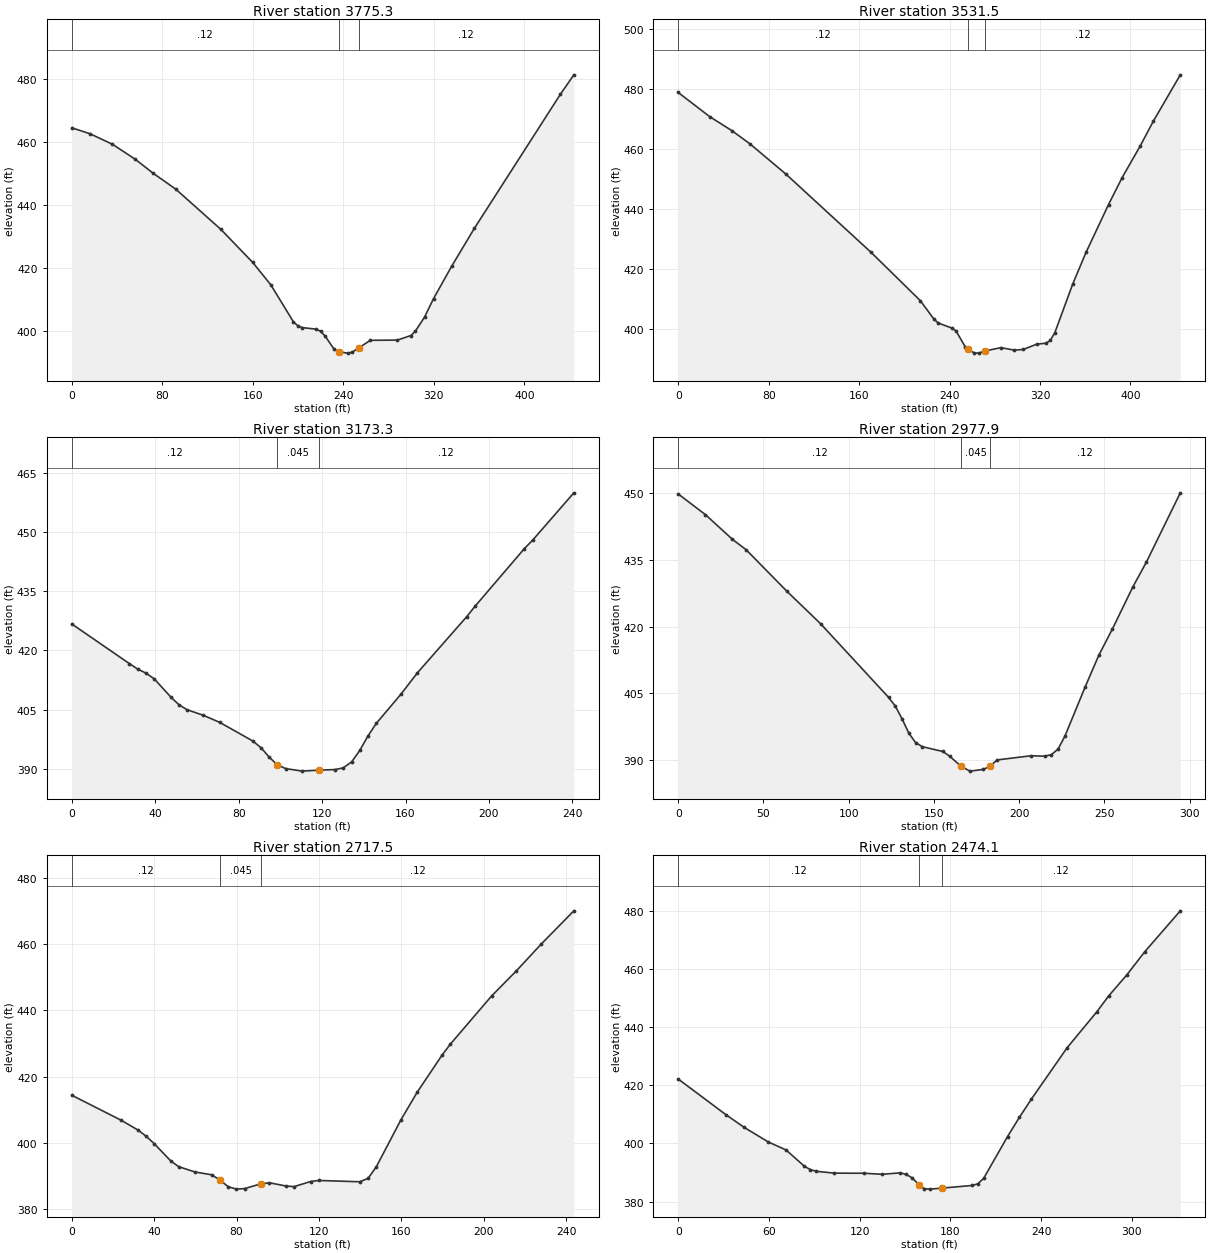
Type RM Length L Ch R = 1 ,3775.3  ,247.3,243.8,272.6
XS GIS Cut Line= 2
     2404471.546      336852.002     2404544.218      336414.219
#Sta/Elev= 30
       0  464.47      16  462.61      36  459.25      56  454.54      72  450.06
      92  445.02   131.9  432.26   159.9  421.84   175.9  414.75   195.9  403.03
   199.9  401.71   203.9  401.17   215.9  400.69   219.9  400.03   223.9  398.52
   231.9  394.32   235.9  393.48   243.9  393.09   247.9  393.38   253.5   394.7
   263.9  397.15   287.8  397.22   299.8  398.67   303.8  400.09   311.8  404.49
   319.8  410.38   335.8  420.62   355.8  432.58   431.8  475.04   443.8  481.26
#Mann= 3 ,-1 , 0
       0     .12       0   235.9    .045       0   253.5     .12       0
Bank Sta=235.9,253.5
XS Rating Curve= 0 ,0
Exp/Cntr=0.3,0.1

Type RM Length L Ch R = 1 ,3531.5  ,355.8,358.3,327.9
XS GIS Cut Line= 2
      2404755.47      336873.065     2404748.517      336429.026
#Sta/Elev= 30
       0  478.86    27.8  470.82    47.6   466.1    63.4  461.75    95.2  451.67
   170.5   425.6   214.1  409.48     226   403.4     230  402.01   241.9  400.35
   245.8  399.34   253.8   394.1     256  393.34   261.7  392.07   265.7  391.98
     271  392.66   285.5  393.81   297.4  392.96   305.3  393.21   317.2  394.98
   325.1  395.27   329.1  396.21   333.1  398.79   348.9  414.98   360.8  425.64
   380.6   441.5   392.6  450.46   408.4  460.88   420.3  469.34   444.1  484.75
#Mann= 3 ,-1 , 0
       0     .12       0     256    .045       0     271     .12       0
Bank Sta=256,271
XS Rating Curve= 0 ,0
Exp/Cntr=0.3,0.1

Type RM Length L Ch R = 1 ,3173.3  ,197.4,195.4,193.2
XS GIS Cut Line= 2
      2405058.59      336713.162      2405068.46      336472.678
#Sta/Elev= 30
       0  426.73    27.6  416.68    31.6  415.28    35.5  414.28    39.5  412.82
    47.4  408.24    51.3  406.27    55.2  404.98    63.1  403.55      71  401.74
    86.8  397.03    90.8   395.3    94.7  392.91    98.6  390.96   102.6  390.03
   110.5  389.39   118.4  389.63   126.3  389.79   130.2  390.23   134.2  391.75
   138.1  394.66     142  398.32     146  401.51   157.8   408.9   165.7  414.33
   189.4  428.61   193.3   431.2     217  445.86     221  448.02   240.7     460
#Mann= 3 ,-1 , 0
       0     .12       0    98.6    .045       0   118.4     .12       0
Bank Sta=98.6,118.4
XS Rating Curve= 0 ,0
Exp/Cntr=0.3,0.1

Type RM Length L Ch R = 1 ,2977.9  ,260.9,260.4,260.7
XS GIS Cut Line= 2
     2405262.857      336787.214     2405241.354      336493.433
#Sta/Elev= 30
       0  449.74    15.9  445.12    31.8  439.57    39.8  437.24    63.7  427.94
    83.6   420.6   123.4  404.12   127.4  402.13   131.4  399.24   135.3  396.08
   139.3  393.95   143.3  393.04   155.2  391.97   159.2  390.94     166  388.62
   171.2  387.56   179.1  387.95   183.1   388.7   187.1  390.07     207  391.01
     215  390.91   218.9  391.24   222.9  392.52   226.9  395.42   238.8  406.48
   246.8  413.58   254.8  419.48   266.7  428.86   274.7  434.46   294.6     450
#Mann= 3 ,-1 , 0
       0     .12       0     166    .045       0   183.1     .12       0
Bank Sta=166,183.1
XS Rating Curve= 0 ,0
Exp/Cntr=0.3,0.1

Type RM Length L Ch R = 1 ,2717.5  ,246.2,243.4,238.3
XS GIS Cut Line= 2
     2405509.121      336697.823     2405497.398      336454.364
#Sta/Elev= 30
       0  414.37      24  406.81      32  403.92      36  402.06      40  399.76
      48  394.58    51.9  392.81    59.9   391.2    67.9  390.37    71.9   388.8
    75.9  386.79    79.9  386.04    83.9  386.21    91.9  387.64    95.9  387.96
   103.9  386.99   107.9  386.79   115.9  388.34   119.9  388.65   139.8  388.26
   143.8  389.28   147.8  392.76   159.8  406.98   167.8  415.41   179.8  426.52
   183.8  429.81   203.8  444.33   215.8  451.89   227.8  459.93   243.7     470
#Mann= 3 ,-1 , 0
       0     .12       0    71.9    .045       0    91.9     .12       0
Bank Sta=71.9,91.9
XS Rating Curve= 0 ,0
Exp/Cntr=0.3,0.1

Type RM Length L Ch R = 1 ,2474.1  ,110.2,109.6,110
XS GIS Cut Line= 3
     2405794.011      336728.555     2405724.355      336603.789
     2405690.463      336417.602
#Sta/Elev= 30
       0  422.14    31.8  409.79    43.7  405.49    59.5  400.52    71.4  397.72
    83.4  392.17    87.3  391.01    91.3  390.42   103.2  389.78     123  389.74
     135  389.38   146.8  389.88   150.8  389.34   154.7  388.16   159.3  385.77
   162.6  384.43   166.6  384.28   174.3  384.62   194.2  385.53   198.1  386.09
     202  387.97   217.8  402.34   225.7     409   233.6  415.25   257.2  432.89
   276.9  445.28   284.8  450.79   296.7  457.95   308.5  465.88   332.1     480
#Mann= 3 ,-1 , 0
       0     .12       0   159.3    .045       0   174.3     .12       0
Bank Sta=159.3,174.3
XS Rating Curve= 0 ,0
Exp/Cntr=0.3,0.1

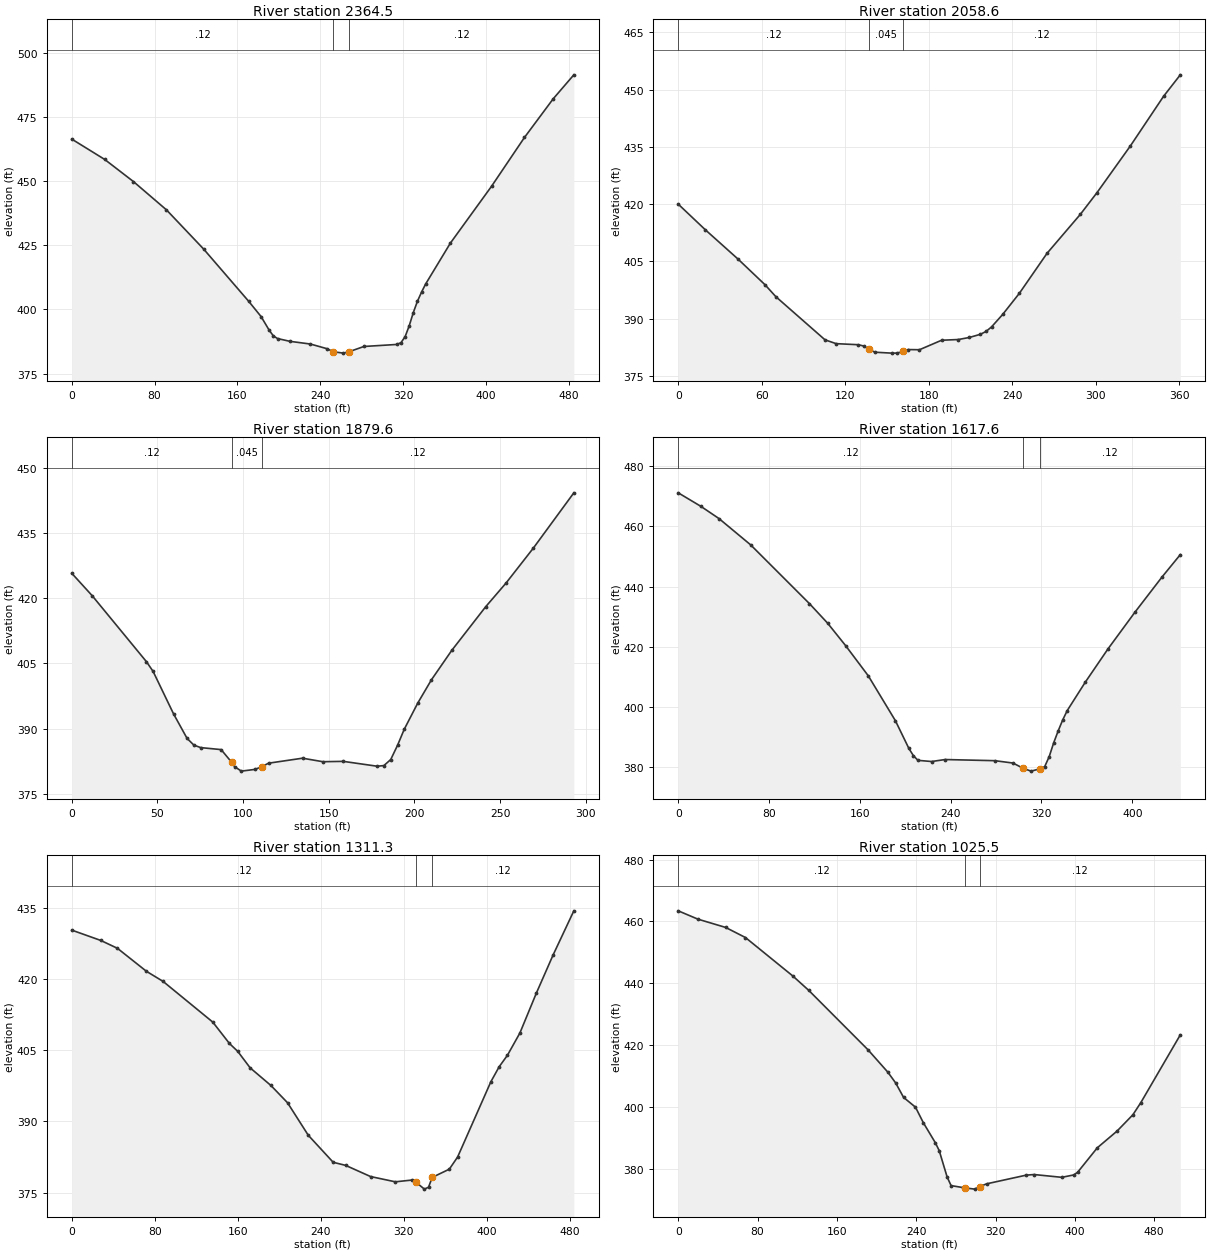
Type RM Length L Ch R = 1 ,2364.5  ,314.5,305.9,298.7
XS GIS Cut Line= 2
     2405889.334      336840.306     2405773.926      336369.456
#Sta/Elev= 30
       0  466.39    31.8  458.46    59.6  449.82    91.4  438.82   127.2  423.59
   170.9  403.14   182.8  397.22   190.7  391.85   194.7  389.67   198.7  388.65
   210.6  387.57   230.5  386.51   246.4   384.7   252.7  383.49   262.3  382.97
   267.7  383.51   282.1  385.56   313.9  386.35   317.9  387.05   321.9  389.41
   325.8  393.59   329.8  398.79   333.8  403.22   337.8   406.8   341.7  409.92
   365.6  425.86   405.3  447.98   437.1  467.02   464.9  482.11   484.8  491.44
#Mann= 3 ,-1 , 0
       0     .12       0   252.7    .045       0   267.7     .12       0
Bank Sta=252.7,267.7
XS Rating Curve= 0 ,0
Exp/Cntr=0.3,0.1

Type RM Length L Ch R = 1 ,2058.6  ,171,178.9,185.1
XS GIS Cut Line= 3
     2406139.747      336693.534     2406103.259      336607.381
     2406024.237      336352.033
#Sta/Elev= 30
       0     420    19.5  413.28    42.9  405.65    62.4   398.9    70.2  395.77
   105.5  384.49   113.5  383.49   129.5  383.21   133.5  382.85   137.4  381.96
   141.4  381.25   153.4  381.01   157.4  381.02   161.4  381.47   165.4  381.94
   173.4   381.9   189.3  384.38   201.3  384.57   209.3  385.11   217.2  385.94
   221.2  386.67   225.2  387.87   233.2  391.13   245.2  396.66   265.1  407.13
     289  417.31     301     423     325  435.23   348.9  448.24   360.9  453.84
#Mann= 3 ,-1 , 0
       0     .12       0   137.4    .045       0   161.4     .12       0
Bank Sta=137.4,161.4
XS Rating Curve= 0 ,0
Exp/Cntr=0.3,0.1

Type RM Length L Ch R = 1 ,1879.6  ,115.7,262,245.3
XS GIS Cut Line= 2
     2406276.445      336607.297     2406192.195      336326.522
#Sta/Elev= 30
       0  425.79    11.9  420.63    43.6  405.41    47.5  403.16    59.4   393.4
    67.3  387.74    71.3  386.18    75.3  385.61    87.2  385.15    93.3  382.25
    95.1  381.21      99  380.19     107  380.59   110.9  381.22   114.9  382.02
   134.7  383.17   146.6  382.36   158.5  382.44   178.3  381.32   182.2  381.47
   186.2  382.86   190.2  386.16   194.1  389.85     202  395.89     210  401.26
   221.8     408   241.6  418.06   253.5  423.53   269.4  431.56   293.1  444.33
#Mann= 3 ,-1 , 0
       0     .12       0    93.3    .045       0   110.9     .12       0
Bank Sta=93.3,110.9
XS Rating Curve= 0 ,0
Exp/Cntr=0.3,0.1

Type RM Length L Ch R = 1 ,1617.6  ,419,306.3,307.3
XS GIS Cut Line= 2
     2406397.476       336710.81     2406296.204      336280.252
#Sta/Elev= 30
       0  471.21    19.9  466.72    35.9  462.64    63.8  453.88   115.6  434.31
   131.5  427.85   147.4  420.35   167.4  410.28   191.3  395.33   203.2  386.07
   207.2  383.66   211.2  382.12   223.2  381.73   235.1  382.39   278.9  382.01
   294.9  381.22     304  379.45   310.8  378.53     319  379.32   322.8     380
   326.8  383.36   330.7   387.9   334.7  391.92   338.7  395.58   342.7  398.71
   358.6  408.16   378.6  419.24   402.5  431.54   426.4  443.28   442.3  450.63
#Mann= 3 ,-1 , 0
       0     .12       0     304    .045       0     319     .12       0
Bank Sta=304,319
XS Rating Curve= 0 ,0
Exp/Cntr=0.3,0.1

Type RM Length L Ch R = 1 ,1311.3  ,288.7,285.8,279.3
XS GIS Cut Line= 2
     2406682.477      336704.848     2406586.525      336230.692
#Sta/Elev= 30
       0  430.24      28  428.06      44  426.41      72  421.56      88  419.44
   135.9  410.87   151.9  406.38   159.9  404.72   171.9  401.24   191.9  397.53
   207.9   393.9   227.9  387.05   251.9  381.36   263.9  380.71   287.9  378.36
   311.8  377.25   327.8  377.62   331.8  377.14   339.8  375.71   343.8  376.12
   347.3  378.18   363.8  379.91   371.8  382.47   403.8   398.3   411.8  401.46
   419.8  403.89   431.8  408.57   447.8  417.04   463.8     425   483.8   434.3
#Mann= 3 ,-1 , 0
       0     .12       0   331.8    .045       0   347.3     .12       0
Bank Sta=331.8,347.3
XS Rating Curve= 0 ,0
Exp/Cntr=0.3,0.1

Type RM Length L Ch R = 1 ,1025.5  ,195.6,204.7,213
XS GIS Cut Line= 2
     2406907.356      336692.324     2406793.097      336198.948
#Sta/Elev= 30
       0  463.43    19.9  460.73    47.8  458.06    67.8  454.79   115.6  442.34
   131.6  437.71   191.4  418.48   211.4  411.24   219.3  407.75   227.3  403.07
   239.3  399.91   247.2  394.89   259.2  388.47   263.2  385.88   271.2  377.33
   275.2  374.54     289  373.81   299.1   373.4     304   374.2     311  375.11
   350.9  377.92   358.9  378.12   386.8  377.22   398.8  377.98   402.8  378.84
   422.7  386.78   442.6  392.18   458.6  397.47   466.6   401.4   506.4  423.31
#Mann= 3 ,-1 , 0
       0     .12       0     289    .045       0     304     .12       0
Bank Sta=289,304
XS Rating Curve= 0 ,0
Exp/Cntr=0.3,0.1