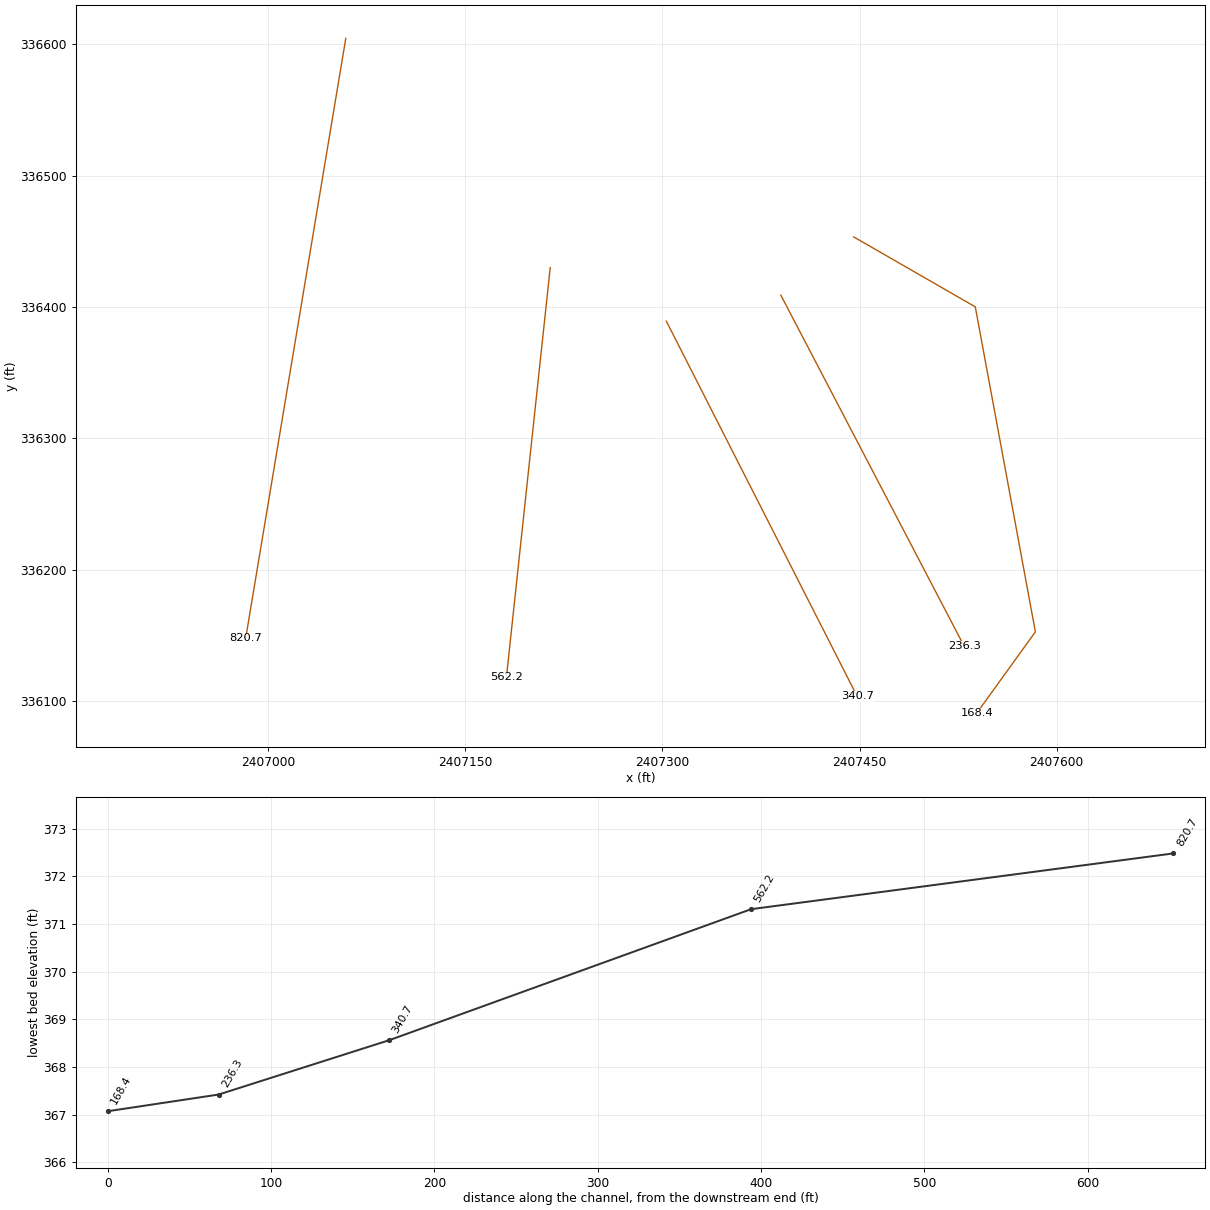
HEC-RAS study COLDSPRING.prj: COLDSPRING

--- COLDSPRING.g01 (geometry) --- (continued)

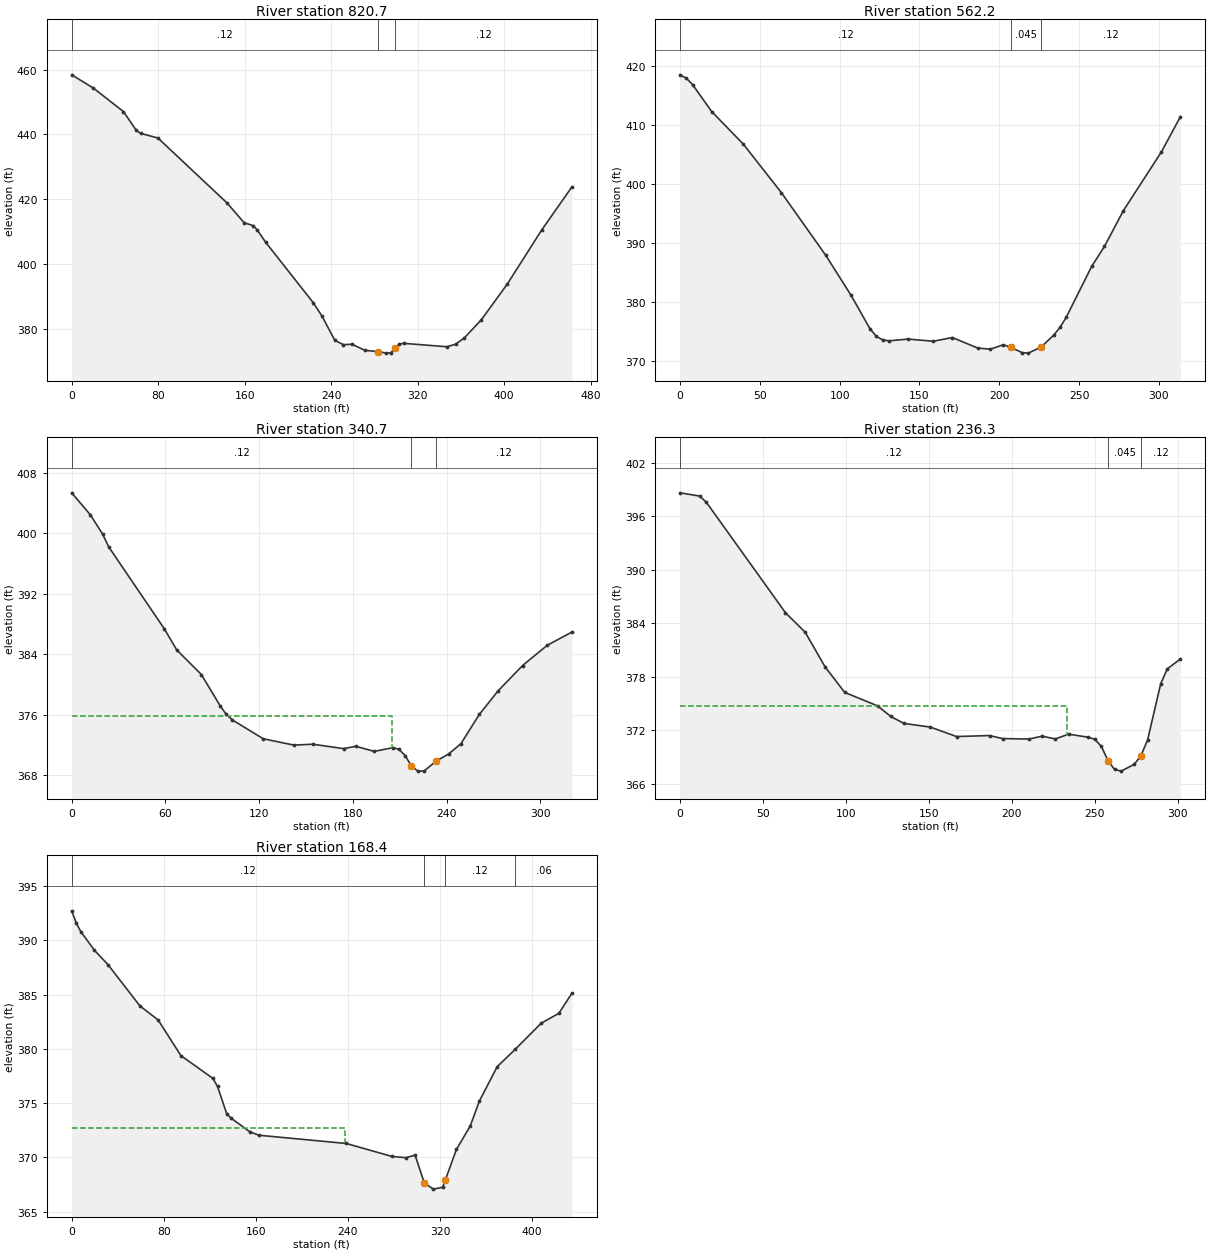
Type RM Length L Ch R = 1 ,820.7   ,245,258.5,256.7
XS GIS Cut Line= 2
     2407059.031      336604.421     2406982.862      336147.962
#Sta/Elev= 30
       0  458.38      20   454.3    47.9  447.03    59.8  441.22    63.8  440.31
    79.8  438.87   143.6  418.86   159.6  412.72   167.6  411.87   171.5  410.59
   179.5  406.67   223.4  388.08   231.4  383.99   243.4  376.44   251.3  375.08
   259.3  375.22   271.3  373.33   283.2  372.96   291.2  372.48   295.2  372.57
   299.2  374.04   303.2   375.3   307.2   375.5   347.1  374.45   355.1  375.22
     363  377.11     379  382.79   402.9  393.77   434.8   410.5   462.8  423.82
#Mann= 3 ,-1 , 0
       0     .12       0   283.2    .045       0   299.2     .12       0
Bank Sta=283.2,299.2
XS Rating Curve= 0 ,0
Exp/Cntr=0.3,0.1

Type RM Length L Ch R = 1 ,562.2   ,224.4,221.6,235.8
XS GIS Cut Line= 2
     2407214.583      336429.967     2407181.253      336118.263
#Sta/Elev= 30
       0  418.43       4  417.84     7.9  416.75    19.8  412.21    39.7  406.67
    63.5  398.47    91.3  387.86   107.1  381.11     119  375.43     123  374.15
     127  373.54     131  373.39   142.8  373.69   158.7  373.32   170.6  373.95
   186.5  372.17   194.4  371.98   202.4  372.72   207.2   372.3   214.3  371.39
   218.2  371.31   226.2  372.33   234.1  374.35   238.1  375.68     242   377.4
   257.9  385.99   265.9  389.37   277.8  395.45   301.6  405.38   313.5  411.34
#Mann= 3 ,-1 , 0
       0     .12       0   207.2    .045       0   226.2     .12       0
Bank Sta=207.2,226.2
XS Rating Curve= 0 ,0
Exp/Cntr=0.3,0.1

Type RM Length L Ch R = 1 ,340.7   ,103.8,104.4,104.5
XS GIS Cut Line= 2
     2407302.943      336389.191     2407448.148      336103.752
#Sta/Elev= 30
       0  405.37    11.9  402.48    19.8  399.91    23.7  398.22    59.3  387.38
    67.2   384.6      83  381.34    94.9  377.24    98.8   376.1   102.8  375.34
   122.6  372.84   142.3     372   154.2  372.12     174  371.54   181.9  371.84
   193.7  371.17   205.6  371.67   209.6  371.44   213.5  370.58   217.4  369.25
   221.4  368.58   225.4  368.56   233.3  369.89   241.2  370.82   249.1  372.18
   260.9  376.06   272.8  379.15   288.6  382.53   304.4  385.21   320.2  386.96
#Mann= 3 ,-1 , 0
       0     .12       0   217.4    .045       0   233.3     .12       0
#XS Ineff= 2 , 0
          205.16  375.87
Permanent Ineff=
       F       F
Bank Sta=217.4,233.3
XS Rating Curve= 0 ,0
Exp/Cntr=0.3,0.1

Type RM Length L Ch R = 1 ,236.3   ,75.9,67.9,60
XS GIS Cut Line= 2
     2407390.064      336408.982     2407529.633      336141.717
#Sta/Elev= 30
       0  398.64    11.9  398.27    15.9  397.56    63.5  385.19    75.4     383
    87.3  379.14    99.2  376.25     119  374.74     127  373.55   134.9  372.77
   150.8  372.36   166.6   371.3   186.5  371.41   194.4  371.07   210.3  371.02
   218.2  371.34   226.1  371.03   234.1  371.57     246  371.22   249.9  370.99
   253.9  370.19   257.9  368.57   261.8  367.61   265.8  367.42   273.7  368.18
   277.7  369.16   281.7  370.89   289.6   377.2   293.6  378.89   301.5     380
#Mann= 3 ,-1 , 0
       0     .12       0   257.9    .045       0   277.7     .12       0
#XS Ineff= 2 , 0
          232.87  374.76
Permanent Ineff=
       F       F
Bank Sta=257.9,277.7
XS Rating Curve= 0 ,0
Exp/Cntr=0.3,0.1

Type RM Length L Ch R = 1 ,168.4   ,150.3,168.4,186.5
XS GIS Cut Line= 4
      2407445.47      336453.344     2407538.013      336400.101
     2407583.747      336152.814     2407539.006      336090.778
#Sta/Elev= 30
       0  392.73       4   391.6     7.9  390.82    19.8  389.09    31.6  387.76
    59.3  383.96    75.1  382.67    94.9  379.38   122.7  377.28   126.7  376.54
   134.7  374.02   138.7   373.6   154.7  372.36   162.6  372.04   238.5  371.28
   278.4  370.08   290.4  369.97   298.4   370.2   306.4  367.63   314.3  367.07
   322.3  367.24   324.5  367.87   334.3  370.73   346.3  372.89   354.2  375.18
   369.7  378.36  385.42379.9664     408  382.37   423.3  383.28   434.7  385.14
#Mann= 4 ,-1 , 0
       0     .12       0   306.4    .045       0   324.5     .12       0
  385.42     .06       0
#XS Ineff= 2 , 0
          237.36  372.75
Permanent Ineff=
       F       F
Bank Sta=306.4,324.5
XS Rating Curve= 0 ,0
Exp/Cntr=0.3,0.1

Chan Stop Cuts=-1
Use User Specified Reach Order=0
Composite Channel Slope=5